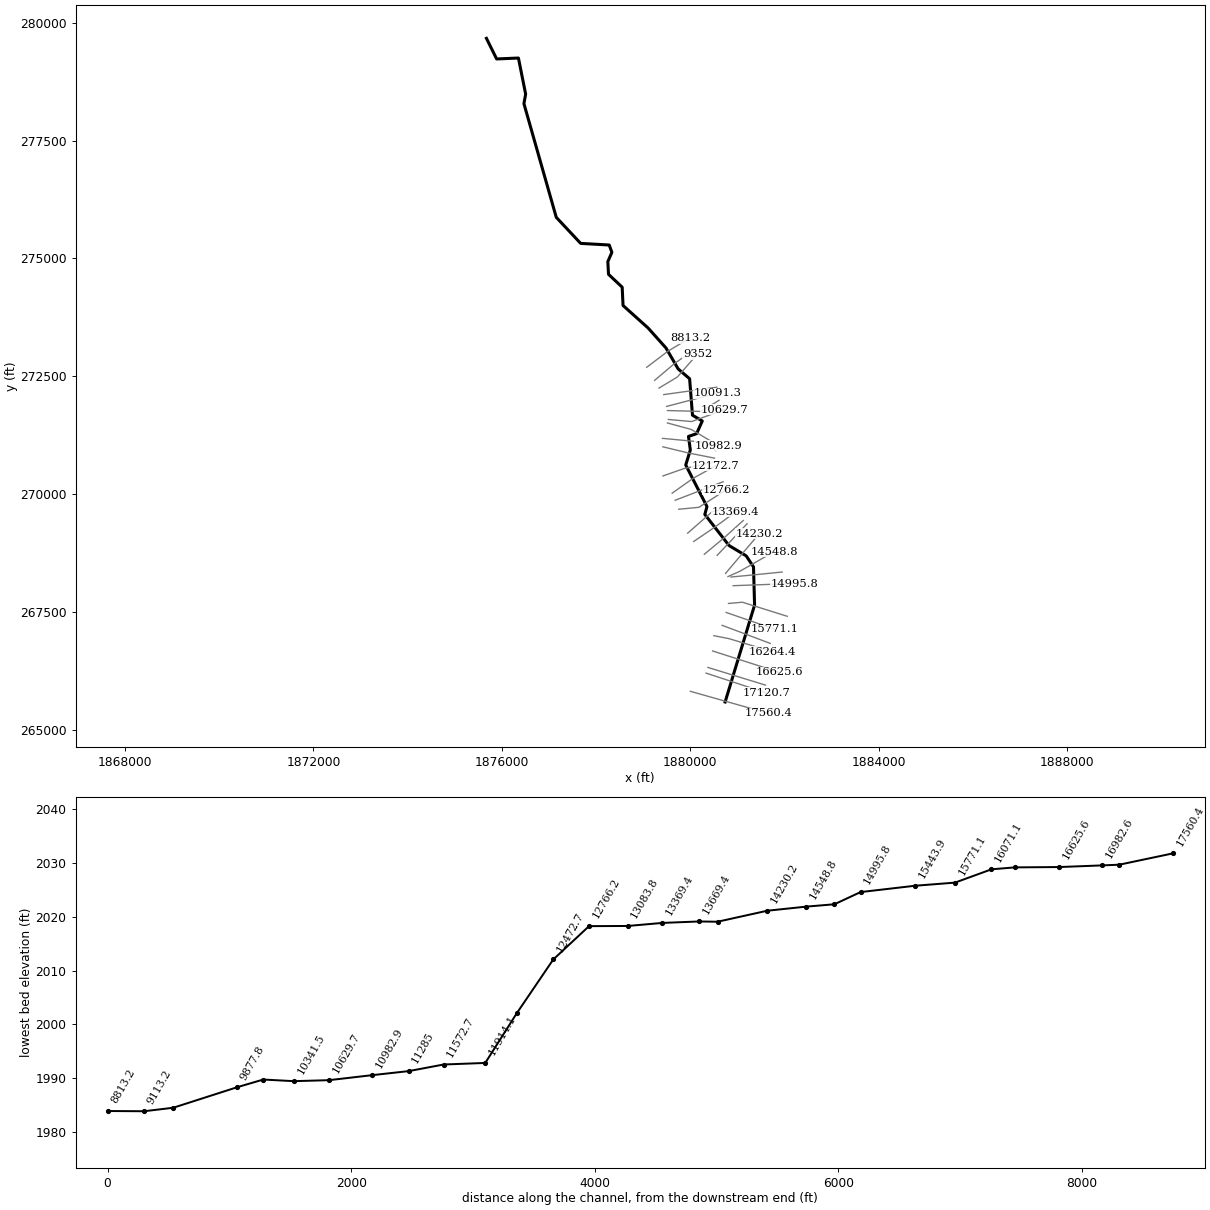
--- SrvyrCrk.prj (project) ---

Proj Title=SrvyrCrk
Current Plan=p01
Default Exp/Contr=0,0
English Units
Geom File=g01
Flow File=f01
Plan File=p01
BEGIN DESCRIPTION:
END DESCRIPTION:
DSS Export Rating Curves= 0
DSS Export Rating Curve Sorted= 0
DSS Export Volume Flow Curves= 0
DXF OffsetX= 0
DXF OffsetY= 0
DXF ScaleX= 0
DXF ScaleY= 0

--- SrvyrCrk.p01 (plan) ---

Plan Title=Floodplain
Program Version=4.00
Geom File=g01
Flow File=f01
K Sum by GR=0
Std Step Tol=0.01
Critical Tol=0.01
Num of Std Step Trials=20
Max Error Tol=0.3
Flow Tol Ratio=0.001
Split Flow NTrial=30
Split Flow Tol=0.02
Split Flow Ratio=0.02
Log Output Level=0
Friction Slope Method=1
Unsteady Friction Slope Method=2
Unsteady Bridges Friction Slope Method=1
Global Log Level=0
CheckData=False
Run HTab=0
Run UNet=0
Run PostProcess=0
UNET Theta=0
UNET Theta Warmup=0
UNET ZTol=0
UNET ZSATol=0
UNET MxIter=0
UNET MaxInSteps=0
UNET DtIC=0
UNET DtMin=0
UNET MaxCRTS=0
UNET WFStab=0
UNET SFStab=0
UNET WFX=0
UNET SFX=0
UNET DSS MLevel=0
UNET DZMax Abort=0
UNET Convert EG Bridges=0
UNET Use Existing IB Tables=0
UNET Froude Limit=0
UNET Froude Power=0
Write IC File=0
Echo Input=False
Echo Output=False
Write Detailed=0

--- SrvyrCrk.f01 (steady flow) ---

Flow Title=NFF Regression Equation
Program Version=4.00
Number of Profiles=1
Profile Names=P100yr
River Rch & RM=SrvyrCrk,Main      ,17560.4
885.6909
River Rch & RM=SrvyrCrk,Main      ,17120.7
897.6510
River Rch & RM=SrvyrCrk,Main      ,16625.6
1082.475
River Rch & RM=SrvyrCrk,Main      ,14995.8
1133.620
River Rch & RM=SrvyrCrk,Main      ,14781.2
1263.216
River Rch & RM=SrvyrCrk,Main      ,11285
1345.312
River Rch & RM=SrvyrCrk,Main      ,10982.9
1505.011
River Rch & RM=SrvyrCrk,Main      ,10629.7
1518.907
River Rch & RM=SrvyrCrk,Main      ,5483.3
1678.975
River Rch & RM=SrvyrCrk,Main      ,4249.7
1834.080
River Rch & RM=SrvyrCrk,Main      ,258.5
1972.907
Boundary for River Rch & Prof#=SrvyrCrk,Main      ,1
Up Type=0
Dn Type=3
Dn Slope=0.008555

--- SrvyrCrk.g01 (geometry) ---

Geom Title=USGS 3m DEM
Program Version=4.10

River Reach=SrvyrCrk        ,Main
Reach XY= 30
     1880740.342      265591.081      1881365.76      267645.547
     1881343.207      268456.967     1881188.259      268690.039
     1880823.676      268910.091     1880309.466      269570.135
     1880354.926      269735.612     1879904.405      270618.425
     1880002.061      270936.133     1879962.619      271223.811
     1880134.915      271282.887     1880255.967      271552.019
     1880047.634      271674.415     1879986.841      272447.775
     1879744.248      272654.883     1879485.134      273100.196
     1879104.237      273525.346      1878573.71      274001.219
     1878555.304      274390.024     1878265.082      274662.696
     1878250.662      274932.514     1878336.696      275128.841
     1878279.891      275284.482     1877673.936      275318.946
     1877156.266      275871.085     1876469.509      278282.487
     1876505.967      278485.612     1876352.913      279250.632
     1875890.322      279230.942     1875673.701      279668.419

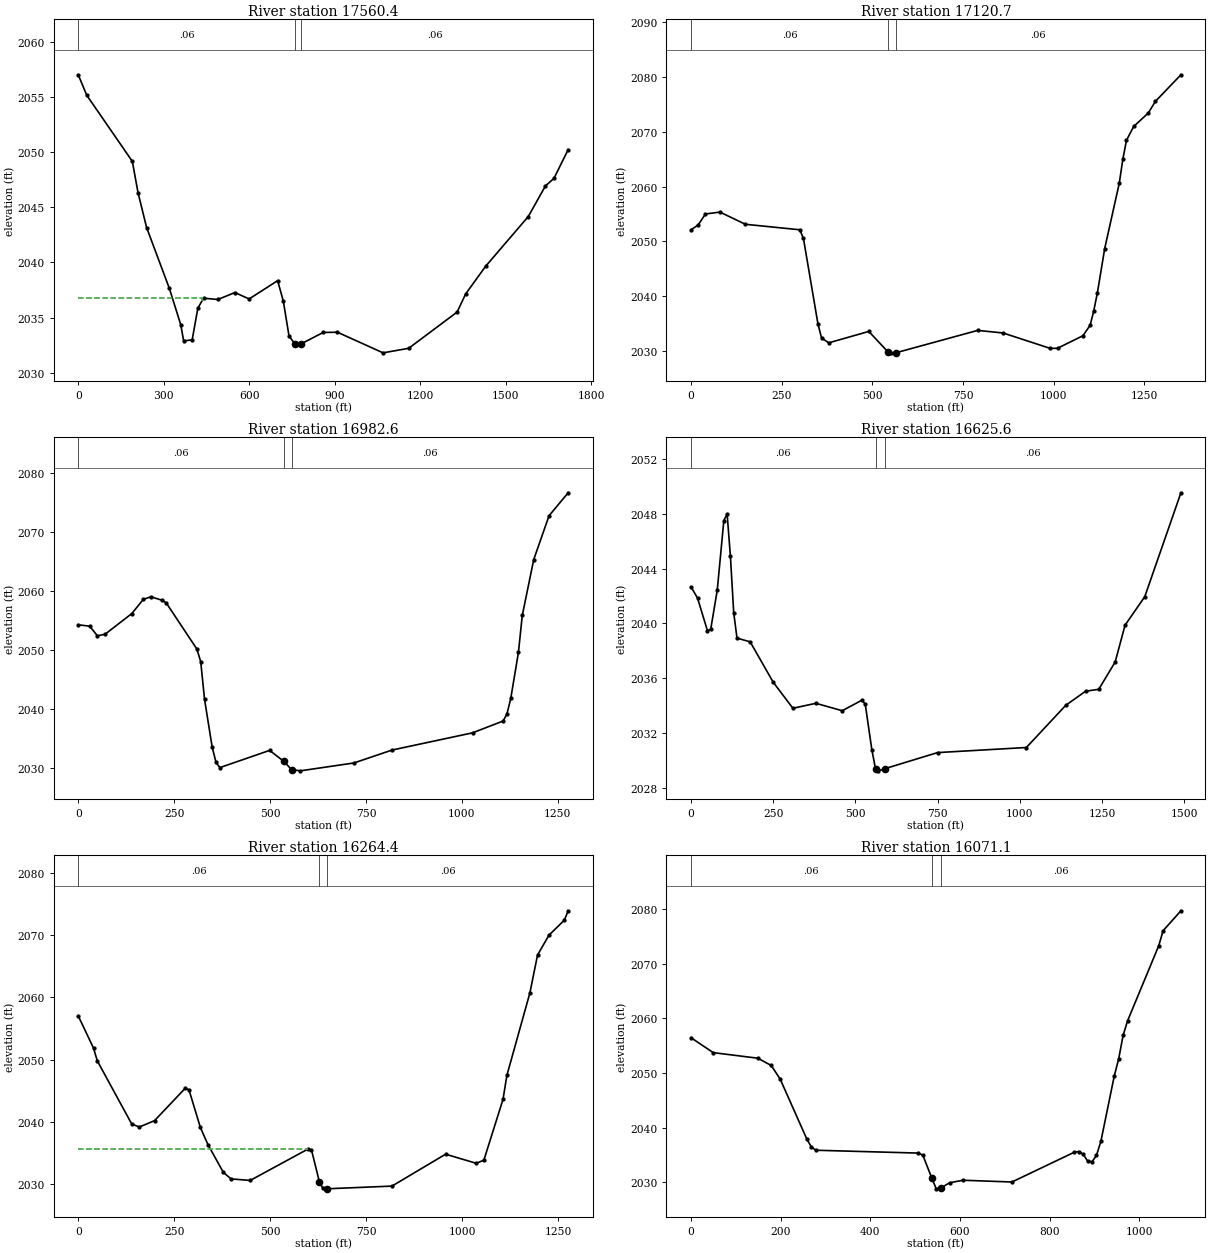
Type RM Length L Ch R = 1 ,17560.4 ,440.8,439.7,438.6
XS GIS Cut Line= 2
     1880003.607      265817.263     1881657.141      265349.541
#Sta/Elev= 30
       0 2057.03      30 2055.17   189.8 2049.17   209.8 2046.32   239.8 2043.17
   319.7 2037.64   359.7 2034.34   369.7 2032.89   399.6 2032.97   419.6 2035.86
   439.6 2036.76   489.6 2036.64   549.5 2037.27   599.4 2036.69   699.4 2038.35
   719.3 2036.49   739.3 2033.33   760.5 2032.59   780.5  2032.6   859.2 2033.65
   909.2 2033.67    1069  2031.8  1158.9 2032.21  1328.8  2035.5  1358.7 2037.14
  1428.7 2039.65  1578.5 2044.17  1638.5 2046.94  1668.5 2047.63  1718.4 2050.24
#Mann= 3 , 0 , 0
       0     .06       0   760.5    .045       0   780.5     .06       0
#XS Ineff= 2 , 0
          434.29 2036.76
Permanent Ineff=
       F       F
Bank Sta=760.5,780.5
XS Rating Curve= 0 ,0
Exp/Cntr=0.3,0.1

Type RM Length L Ch R = 1 ,17120.7 ,137.6,138.1,138.7
XS GIS Cut Line= 2
     1880335.334       266203.78     1881618.622      265781.496
#Sta/Elev= 30
       0  2052.1      20 2053.02      40 2055.01    80.1 2055.35   150.1 2053.13
   300.2 2052.13   310.2 2050.54   350.2 2034.96   360.3 2032.37   380.3 2031.53
   490.4  2033.6   544.3  2029.8   550.4  2029.7   564.3  2029.7   790.6 2033.79
   860.6 2033.32   990.7 2030.51  1010.7 2030.53  1080.8 2032.82  1100.8 2034.73
  1110.8 2037.39  1120.8 2040.68  1140.8 2048.69  1180.9 2060.58  1190.9    2065
  1200.9 2068.45  1220.9 2070.97  1260.9  2073.4  1280.9 2075.55    1351 2080.38
#Mann= 3 , 0 , 0
       0     .06       0   544.3    .045       0   564.3     .06       0
Bank Sta=544.3,564.3
XS Rating Curve= 0 ,0
Exp/Cntr=0.3,0.1

Type RM Length L Ch R = 1 ,16982.6 ,357.2,356.9,356.6
XS GIS Cut Line= 2
     1880375.669      266323.863     1881596.612      265949.326
#Sta/Elev= 30
       0 2054.29    29.9 2054.05    49.9 2052.43    69.8 2052.68   139.7 2056.19
   169.6 2058.58   189.6 2059.03   219.5 2058.42   229.5 2057.98   309.3 2050.18
   319.3 2048.02   329.2 2041.69   349.2 2033.56   359.2 2030.99   369.2 2030.12
   498.9 2033.03     536 2031.17     556 2029.78   578.7 2029.57   718.4  2030.9
   818.1 2033.09  1027.7    2036  1107.5    2038  1117.5  2039.2  1127.4 2041.82
  1147.4 2049.61  1157.4 2055.87  1187.3 2065.33  1227.2 2072.75  1277.1 2076.63
#Mann= 3 , 0 , 0
       0     .06       0     536    .045       0     556     .06       0
Bank Sta=536,556
XS Rating Curve= 0 ,0
Exp/Cntr=0.3,0.1

Type RM Length L Ch R = 1 ,16625.6 ,360.6,361,361.5
XS GIS Cut Line= 2
     1880474.977      266673.248     1881893.753      266218.953
#Sta/Elev= 30
       0 2042.67      20 2041.85      50 2039.48      60 2039.56      80 2042.43
     100  2047.5     110 2047.97     120 2044.89     130 2040.78     140 2038.93
     180 2038.66     250 2035.72   309.9 2033.82   379.9 2034.18   459.9 2033.64
   519.9 2034.41   529.9 2034.12   549.9 2030.81   561.3 2029.39   569.9 2029.26
   589.9 2029.42   749.9 2030.59  1019.8 2030.96  1139.8 2034.04  1199.8 2035.06
  1239.8  2035.2  1289.8 2037.19  1319.8 2039.87  1379.8 2041.95  1489.7 2049.52
#Mann= 3 , 0 , 0
       0     .06       0   561.3    .045       0   589.9     .06       0
Bank Sta=561.3,589.9
XS Rating Curve= 0 ,0
Exp/Cntr=0.3,0.1

Type RM Length L Ch R = 1 ,16264.4 ,194.9,193.2,191.5
XS GIS Cut Line= 3
     1880501.593      266997.572     1880823.496      266934.292
     1881731.426      266661.913
#Sta/Elev= 30
       0 2057.02    39.8 2051.83    49.7 2049.78   139.2 2039.64   159.1 2039.14
   198.8 2040.17   278.4 2045.36   288.3 2045.15   318.1 2039.07     338 2036.29
     378 2031.84   397.9  2030.8   447.8 2030.55   597.5 2035.57   607.4 2035.48
   628.1 2030.31   637.4 2029.27   647.4  2029.2   648.1 2029.21     817 2029.64
   956.7 2034.77  1036.5 2033.31  1056.4 2033.81  1106.3  2043.6  1116.3 2047.44
  1176.2  2060.7  1196.2 2066.81  1226.1 2070.01    1266 2072.41    1276 2073.92
#Mann= 3 , 0 , 0
       0     .06       0   628.1    .045       0   648.1     .06       0
#XS Ineff= 2 , 0
          599.53 2035.64
Permanent Ineff=
       F       F
Bank Sta=628.1,648.1
XS Rating Curve= 0 ,0
Exp/Cntr=0.3,0.1

Type RM Length L Ch R = 1 ,16071.1 ,299.4,300,300.7
XS GIS Cut Line= 3
     1880675.904      267217.576     1881188.342       267025.82
     1881698.966      266833.635
#Sta/Elev= 30
       0 2056.45    49.7 2053.72   149.2  2052.7   179.1 2051.37     199 2048.88
   258.6  2037.9   268.6 2036.48   278.5 2035.89   507.4 2035.37   517.3 2034.96
   537.1  2030.8   547.1 2028.84   557.1 2028.99   576.9 2029.95   606.7 2030.41
   715.8 2030.09   854.7 2035.52   864.6 2035.65   874.5 2035.19   884.4 2033.94
   894.3 2033.78   904.3 2034.93   914.2 2037.51   943.9 2049.39   953.9 2052.59
   963.8 2056.87   973.7 2059.52  1043.1 2073.22    1053 2075.99  1092.7 2079.63
#Mann= 3 , 0 , 0
       0     .06       0   537.1    .045       0   557.1     .06       0
Bank Sta=537.1,557.1
XS Rating Curve= 0 ,0
Exp/Cntr=0.3,0.1

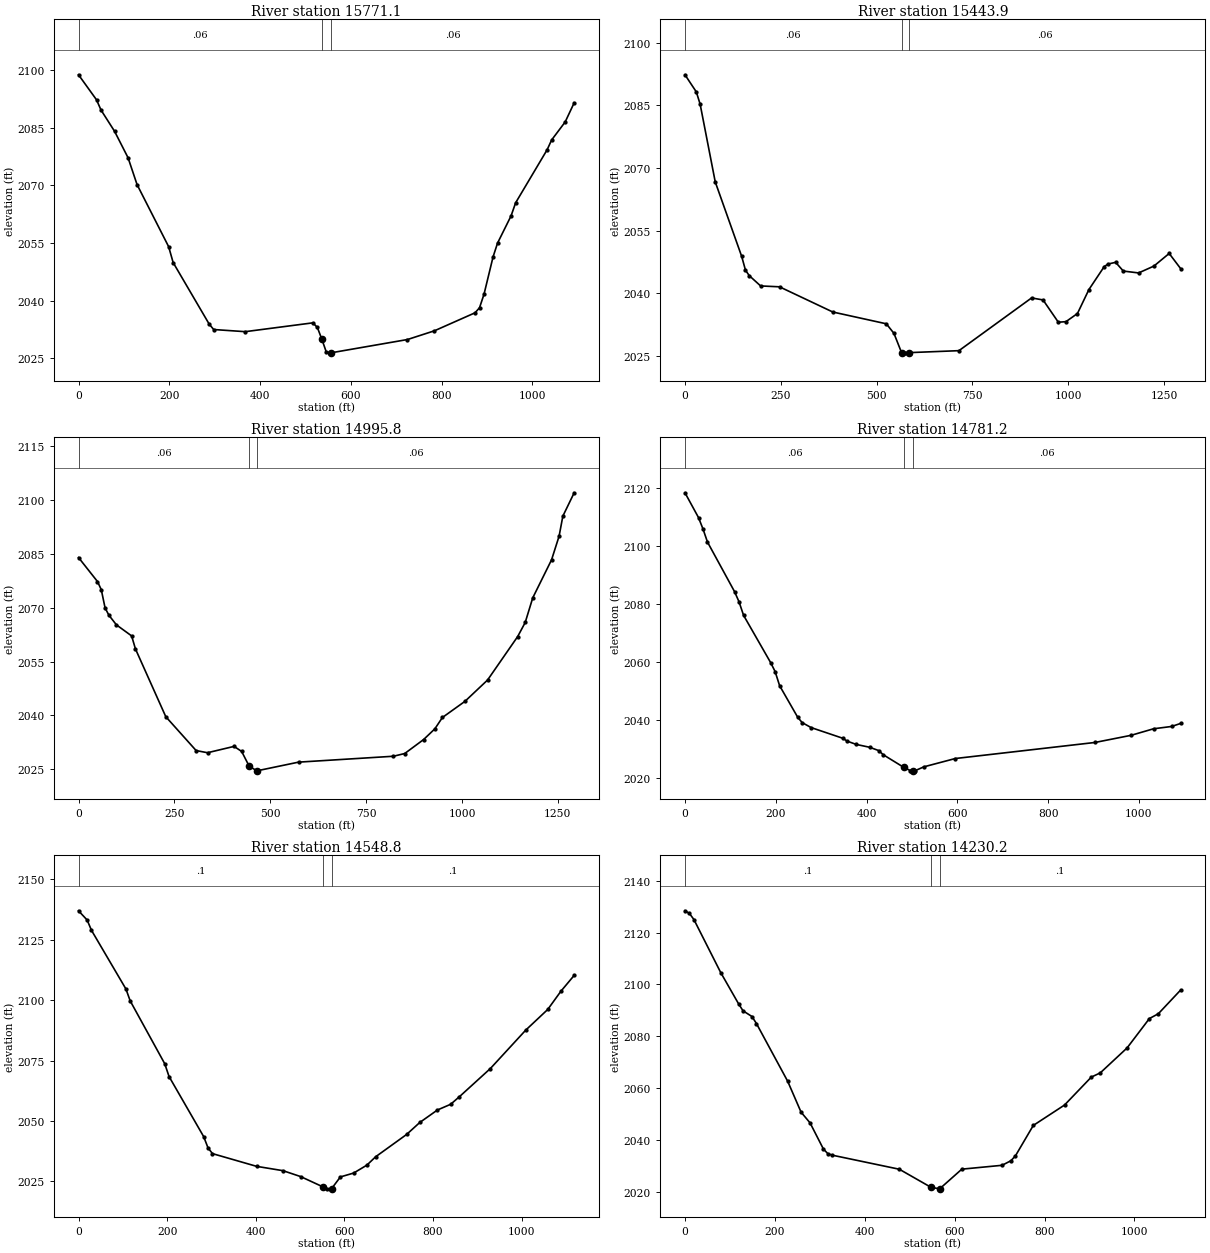
Type RM Length L Ch R = 1 ,15771.1 ,326.5,327.2,327.9
XS GIS Cut Line= 3
     1880762.837      267490.249     1881278.847      267311.784
     1881794.857      267133.319
#Sta/Elev= 30
       0 2098.87    39.7 2092.34    49.6 2089.67    79.4 2084.14   109.2 2077.22
     129 2070.23   198.6 2054.04   208.5  2049.9   287.9 2033.85   297.8 2032.44
   367.3 2031.88   516.2 2034.18   526.2 2032.99     536 2029.94     546 2026.54
   555.9 2026.36     556 2026.36   724.7 2029.83   784.2 2032.11   873.6  2036.8
   883.5 2038.12   893.4 2041.65   913.3 2051.37   923.2 2054.98     953 2062.08
     963 2065.48  1032.4 2079.31  1042.4 2081.88  1072.2 2086.57    1092 2091.56
#Mann= 3 , 0 , 0
       0     .06       0     536    .045       0     556     .06       0
Bank Sta=536,556
XS Rating Curve= 0 ,0
Exp/Cntr=0.3,0.1

Type RM Length L Ch R = 1 ,15443.9 ,439.5,448.1,456.7
XS GIS Cut Line= 3
     1880812.429      267681.169      1881107.31      267707.451
     1882059.089      267408.763
#Sta/Elev= 30
       0 2092.32    29.6 2088.22    39.5 2085.31      79 2066.68     148 2048.86
   157.9 2045.56   167.8 2044.25   197.4 2041.79   246.7 2041.58   385.8 2035.55
   525.5 2032.73   545.4 2030.44   565.4  2025.8   575.4 2025.78   585.3 2025.83
     715  2026.3   904.6 2038.92   934.5 2038.44   974.4 2033.11   994.3 2033.24
  1024.3 2035.19  1054.2 2040.92  1094.1 2046.41  1104.1 2047.03    1124 2047.44
    1144 2045.35  1183.9  2044.9  1223.8 2046.54  1263.7 2049.56  1293.6 2045.94
#Mann= 3 , 0 , 0
       0     .06       0   565.4    .045       0   585.3     .06       0
Bank Sta=565.4,585.3
XS Rating Curve= 0 ,0
Exp/Cntr=0.3,0.1

Type RM Length L Ch R = 1 ,14995.8 ,213.1,214.5,216
XS GIS Cut Line= 3
     1880911.318      268057.868     1881741.829      268088.163
     1882203.016      268102.092
#Sta/Elev= 30
       0 2083.95    49.5 2077.26    59.4 2074.99    69.3 2069.92    79.2  2067.9
    98.9 2065.21   138.5 2062.14   148.4 2058.54   227.6 2039.66   306.7 2030.24
   336.4 2029.64   405.6  2031.4   425.4    2030     445 2025.91     465  2024.6
   573.8 2027.02   821.2 2028.66   850.7 2029.42   899.8  2033.3   929.2 2036.28
   948.9 2039.44  1007.8 2043.94  1066.7 2049.87  1145.2 2061.96  1164.8 2065.87
  1184.5 2072.73  1233.6 2083.32  1253.2  2089.9    1263 2095.46  1292.5 2101.96
#Mann= 3 , 0 , 0
       0     .06       0     445    .045       0     465     .06       0
Bank Sta=445,465
XS Rating Curve= 0 ,0
Exp/Cntr=0.3,0.1

Type RM Length L Ch R = 1 ,14781.2 ,221.7,232.3,243
XS GIS Cut Line= 3
     1880864.183      268241.729     1881407.733      268293.476
     1881951.021      268347.805
#Sta/Elev= 30
       0 2118.45    29.8 2109.88    39.7 2105.93    49.6 2101.41   109.2 2084.28
   119.1 2080.76   129.1 2076.08   188.6 2059.78   198.6 2056.65   208.5 2051.76
   248.2 2040.89   258.1 2039.01     278 2037.28   347.5  2033.6   357.4 2032.59
   377.2 2031.47     407 2030.47   426.9 2029.33   436.8  2027.9   482.1 2023.53
   496.4 2022.42   502.1 2022.37   506.3 2022.33   526.2 2023.71   595.6 2026.59
   903.4 2032.14   982.8 2034.61  1032.4 2036.87  1072.2 2037.67    1092 2038.72
#Mann= 3 , 0 , 0
       0     .06       0   482.1    .045       0   502.1     .06       0
Bank Sta=482.1,502.1
XS Rating Curve= 0 ,0
Exp/Cntr=0.3,0.1

Type RM Length L Ch R = 1 ,14548.8 ,309.1,318.6,328.1
XS GIS Cut Line= 3
     1880801.408       268250.82     1881050.048       268362.09
     1881784.899      268781.336
#Sta/Elev= 30
       0 2136.96    19.5 2133.13    29.2 2128.89     107 2104.59   116.7 2099.64
   194.6 2073.65   204.3 2068.36   282.4  2043.5   292.3 2038.81   302.3 2036.46
   401.8  2031.2   461.5  2029.4   501.3 2026.96   551.1 2022.74     561 2021.89
     571 2021.95   590.9 2026.82   620.8 2028.42   650.6 2031.69   670.5 2035.17
   740.2 2044.38   770.1 2049.36   809.9 2054.52   839.7 2056.88   859.6 2060.04
   929.3 2071.67    1009 2087.55  1058.7 2096.11  1088.6 2103.69  1118.4 2110.22
#Mann= 3 , 0 , 0
       0      .1       0   551.1    .045       0     571      .1       0
Bank Sta=551.1,571
XS Rating Curve= 0 ,0
Exp/Cntr=0.3,0.1

Type RM Length L Ch R = 1 ,14230.2 ,412.1,408.8,408.5
XS GIS Cut Line= 2
     1880749.586      268318.723     1881462.996      269159.591
#Sta/Elev= 30
       0  2128.4     9.9 2127.38    19.9 2125.01    79.5 2104.57   119.2 2092.52
   129.2  2089.8     149 2087.61     159  2084.9   228.5 2062.63   258.3  2050.7
   278.2 2046.59     308 2036.48   317.9 2034.69   327.8 2034.11   476.9 2028.69
   547.1 2021.74   566.3 2021.13   567.1 2021.21   615.9 2028.72   705.4 2030.21
   725.2 2031.98   735.2 2033.86   774.9 2045.59   844.4 2053.46     904 2064.24
   923.9 2065.86   983.5 2075.48  1033.2 2086.82  1053.1 2088.68  1102.7 2097.82
#Mann= 3 , 0 , 0
       0      .1       0   547.1    .045       0   567.1      .1       0
Bank Sta=547.1,567.1
XS Rating Curve= 0 ,0
Exp/Cntr=0.3,0.1

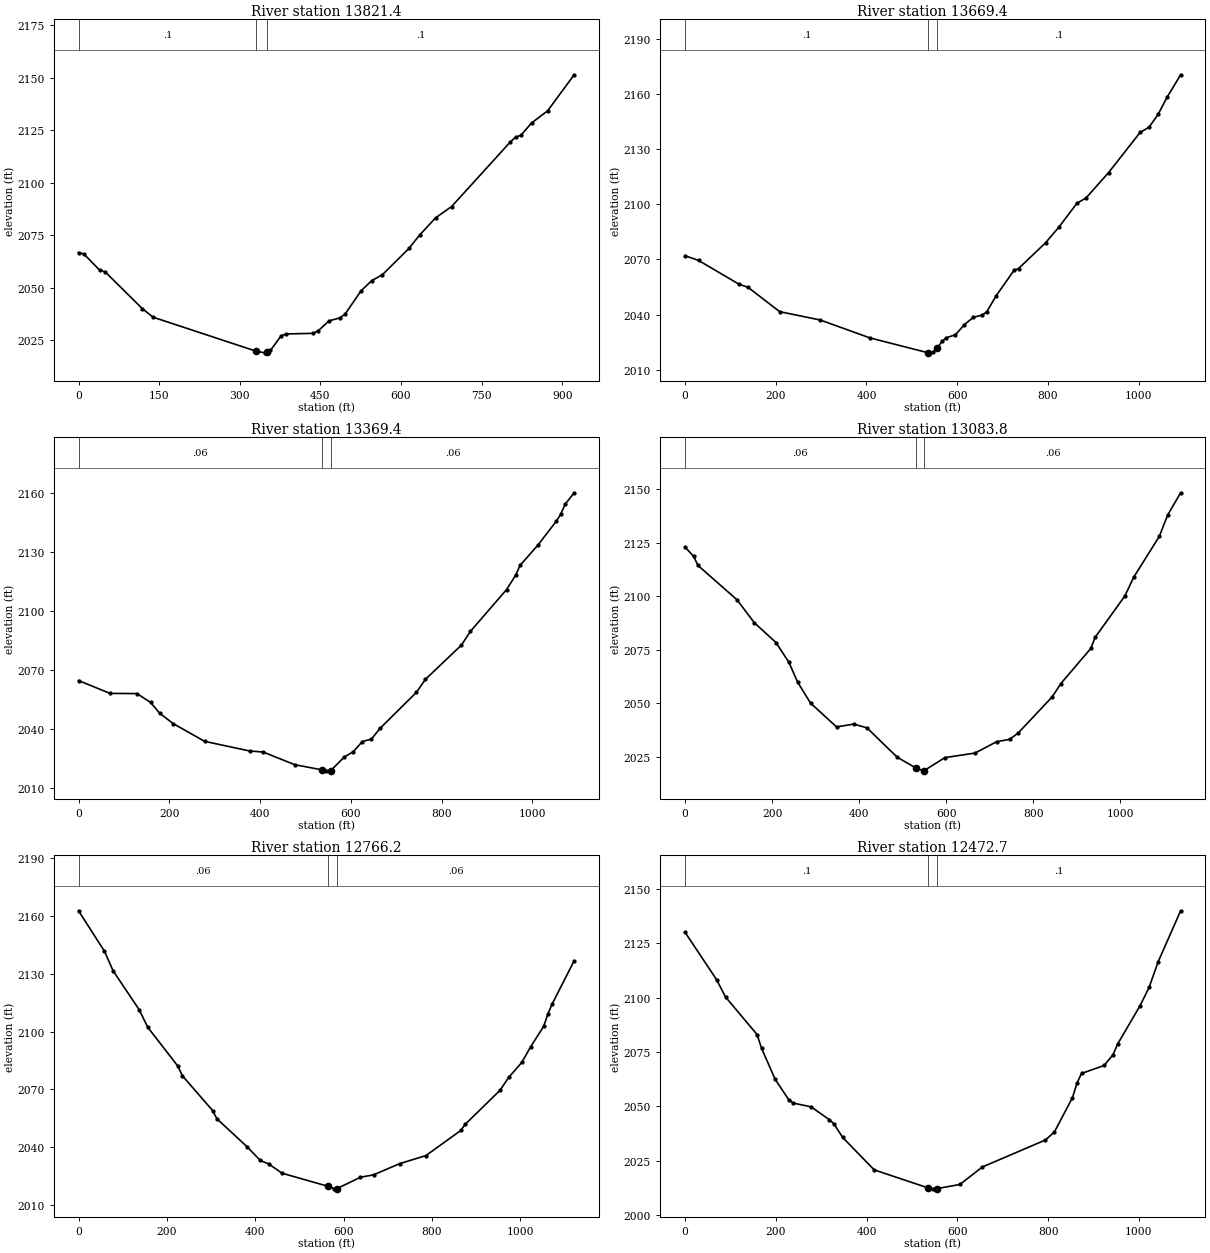
Type RM Length L Ch R = 1 ,13821.4 ,155.5,152,149.9
XS GIS Cut Line= 2
     1880571.837      268702.564     1881206.669      269371.387
#Sta/Elev= 30
       0 2066.76     9.9 2066.13    39.7  2058.3    49.6 2057.58     119 2040.04
   138.8 2036.02   330.7 2019.84     347 2019.08   350.7 2019.49     357  2020.2
   376.8 2027.12   386.7 2028.07   436.3 2028.35   446.2 2029.62     466 2034.27
   485.9  2035.7   495.8 2037.46   525.5 2048.52   545.4 2053.41   565.2  2056.2
   614.8 2068.74   634.6 2075.11   664.3 2083.28   694.1 2088.66   803.2 2119.33
   813.1 2121.65     823 2122.52   842.8 2128.39   872.6 2134.15   922.1 2151.32
#Mann= 3 , 0 , 0
       0      .1       0   330.7    .045       0   350.7      .1       0
Bank Sta=330.7,350.7
XS Rating Curve= 0 ,0
Exp/Cntr=0.3,0.1

Type RM Length L Ch R = 1 ,13669.4 ,302.4,300,297.4
XS GIS Cut Line= 3
     1880299.029       268724.87     1880719.352       269073.97
     1881124.804       269439.57
#Sta/Elev= 30
       0 2072.03    29.8 2069.48   119.2 2056.48   139.1  2054.8   208.6 2041.56
     298 2037.02   407.3 2027.28   536.4 2019.13   546.4 2019.47   556.4 2021.78
   566.2 2025.36   576.2  2027.4     596 2028.96   615.9 2034.52   635.7 2038.52
   655.6  2039.7   665.5 2041.64   685.4  2050.1   725.1 2064.05     735 2065.02
   794.6 2079.06   824.3  2087.7     864 2100.65   883.9 2103.48   933.5 2117.28
    1003 2139.17  1022.8 2142.03  1042.7 2149.03  1062.6  2158.4  1092.3 2170.57
#Mann= 3 , 0 , 0
       0      .1       0   536.4    .045       0   556.4      .1       0
Bank Sta=536.4,556.4
XS Rating Curve= 0 ,0
Exp/Cntr=0.3,0.1

Type RM Length L Ch R = 1 ,13369.4 ,282.6,285.6,287.8
XS GIS Cut Line= 3
     1880073.526      268995.596     1880525.077      269302.418
     1880966.033      269625.086
#Sta/Elev= 30
       0 2064.73    69.5 2058.22     129 2058.11   158.8 2053.62   178.7 2048.18
   208.4  2042.9   277.9 2033.85   377.2 2028.95     407 2028.41   476.4    2022
   535.9 2019.38   545.9 2018.86   555.9 2019.01   585.7 2025.88   605.5 2028.59
   625.4 2033.73   645.3 2034.99   665.1 2040.59   744.6 2058.73   764.5 2065.36
     844 2082.78   863.8 2089.78   943.3 2110.96   963.2  2118.2   973.1 2123.27
  1012.9 2133.71  1052.6 2145.64  1062.5 2149.15  1072.5 2154.36  1092.3 2160.16
#Mann= 3 , 0 , 0
       0     .06       0   535.9    .045       0   555.9     .06       0
Bank Sta=535.9,555.9
XS Rating Curve= 0 ,0
Exp/Cntr=0.3,0.1

Type RM Length L Ch R = 1 ,13083.8 ,320.7,317.5,314.2
XS GIS Cut Line= 3
     1879945.952      269172.359     1880469.695      269631.128
     1880902.382      269721.457
#Sta/Elev= 30
       0  2123.1    19.9  2118.7    29.8 2114.45   119.4 2098.37   159.1 2087.66
   208.9 2078.37   238.7  2069.1   258.6 2059.84   288.4 2049.98   348.1 2038.85
   387.9 2040.18   417.8 2038.42   487.4 2024.67   529.5 2019.71   547.1 2018.29
   549.5 2018.43   596.8 2024.47   666.4 2026.63   715.9 2031.95   745.4 2033.02
     765 2035.96   843.6 2052.99   863.2 2059.14     932 2075.59   941.8 2080.73
  1010.6 2100.27  1030.2 2108.82  1089.2    2128  1108.8 2138.17  1138.3 2148.46
#Mann= 3 , 0 , 0
       0     .06       0   529.5    .045       0   549.5     .06       0
Bank Sta=529.5,549.5
XS Rating Curve= 0 ,0
Exp/Cntr=0.3,0.1

Type RM Length L Ch R = 1 ,12766.2 ,298.6,293.5,288.4
XS GIS Cut Line= 3
     1879756.209      269679.468     1880184.935       269720.89
     1880766.676      270093.575
#Sta/Elev= 30
       0 2162.75    58.7 2141.76    78.3 2131.55     137 2111.45   156.6 2102.24
   225.2 2081.91   234.9 2077.06   303.5 2058.93   313.2 2054.65   381.8 2040.06
   411.1 2033.03   430.7 2031.17   460.3  2026.4   564.5 2019.58   578.8 2018.26
   584.5 2018.34     638 2024.29   667.6 2025.52   726.8 2031.36     786 2035.52
     865 2048.58   874.9 2051.77   953.8 2069.45   973.6  2076.2  1003.2 2083.98
  1022.9    2092  1052.5 2102.66  1062.4 2109.23  1072.2  2114.5  1121.6 2136.77
#Mann= 3 , 0 , 0
       0     .06       0   564.5    .045       0   584.5     .06       0
Bank Sta=564.5,584.5
XS Rating Curve= 0 ,0
Exp/Cntr=0.3,0.1

Type RM Length L Ch R = 1 ,12472.7 ,293.8,300,303.4
XS GIS Cut Line= 3
     1879680.174      269869.782     1880189.458      270066.612
     1880698.822      270263.256
#Sta/Elev= 30
       0  2130.1    69.5 2108.31    89.3  2100.3   158.8 2083.03   168.8 2076.64
   198.5 2062.52   228.3 2053.13   238.2 2051.51     278 2049.76   317.7 2043.92
   327.6 2042.08   347.4 2035.71   416.9 2020.78     536 2012.47     546 2012.06
     556 2012.21   605.6 2014.06   655.2 2022.11   794.2 2034.53     814 2038.26
   853.7    2054   863.7  2060.7   873.6 2065.11   923.2 2068.79   943.1 2073.73
     953 2078.59  1002.6 2096.28  1022.5 2104.69  1042.4 2116.46    1092 2139.94
#Mann= 3 , 0 , 0
       0      .1       0     536    .045       0     556      .1       0
Bank Sta=536,556
XS Rating Curve= 0 ,0
Exp/Cntr=0.3,0.1

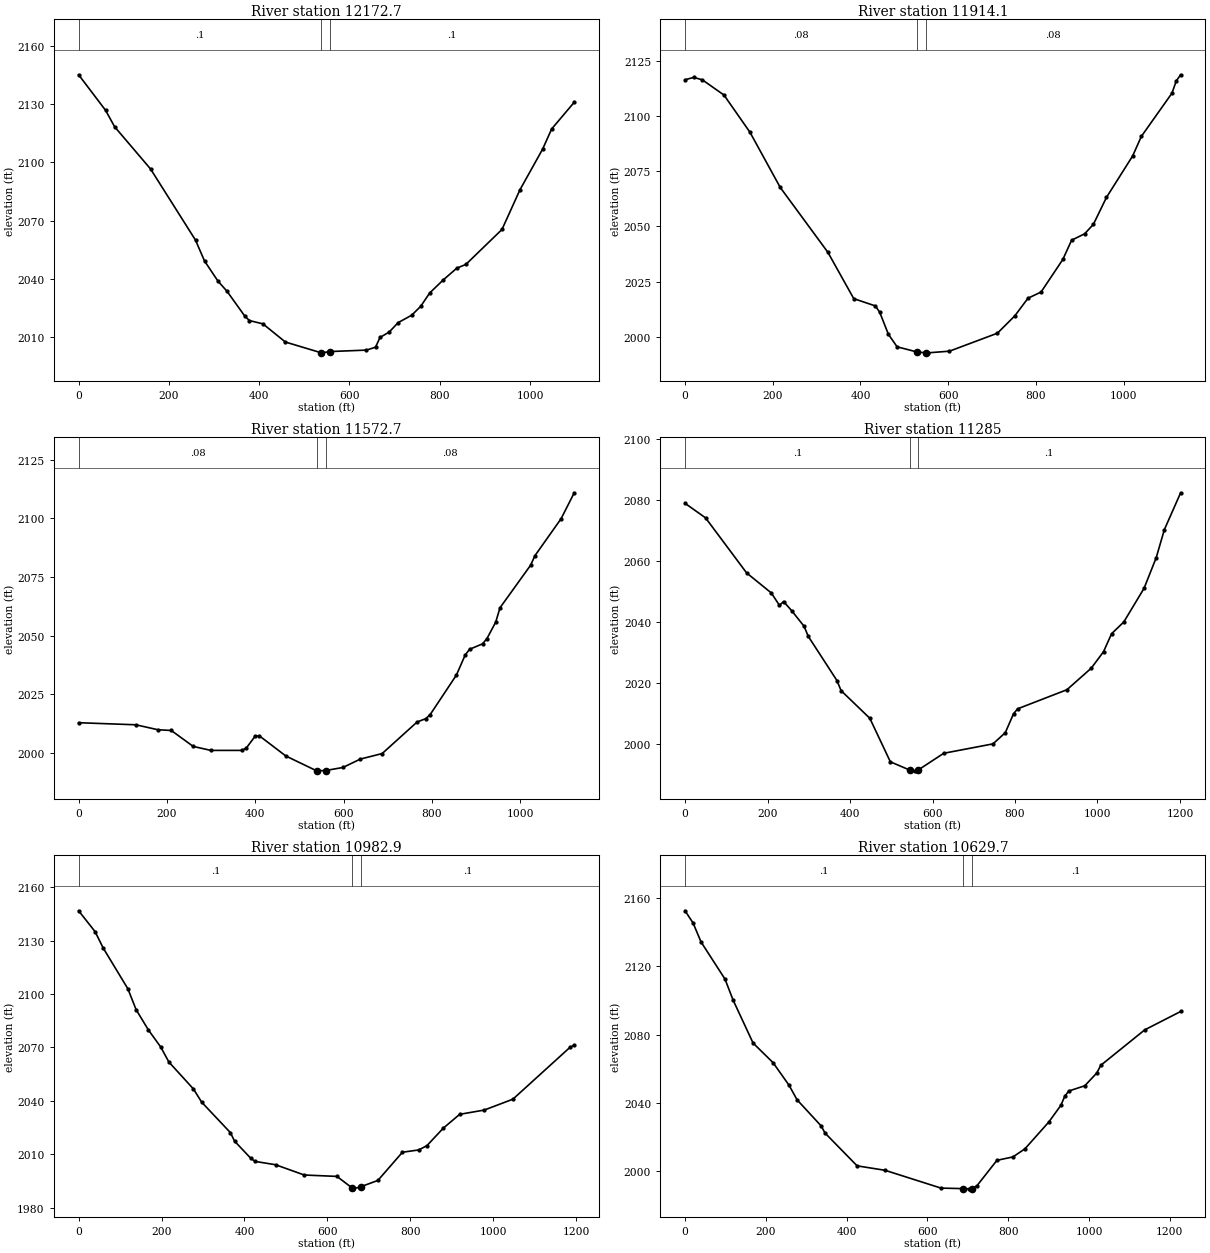
Type RM Length L Ch R = 1 ,12172.7 ,268.6,258.6,251.4
XS GIS Cut Line= 3
     1879616.064      270020.451     1880063.113      270337.013
     1880544.736      270603.246
#Sta/Elev= 30
       0 2145.02    59.8 2126.71    79.7  2118.3   159.4 2096.57     259 2059.98
   278.9 2049.29   308.8  2038.9   328.7 2033.72   368.5 2020.82   378.5 2018.64
   408.4 2016.93   458.1  2007.6   537.8 2002.04   557.8 2002.71   637.8 2003.45
   657.8 2004.94   667.8 2009.98   687.9 2012.68   707.9 2017.57   737.9 2021.38
   757.9 2025.95   777.9 2032.83   807.9 2039.54   837.9 2045.58     858 2047.51
     938 2065.47     978 2085.96    1028 2106.76  1048.1 2117.17  1098.1 2130.89
#Mann= 3 , 0 , 0
       0      .1       0   537.8    .045       0   557.8      .1       0
Bank Sta=537.8,557.8
XS Rating Curve= 0 ,0
Exp/Cntr=0.3,0.1

Type RM Length L Ch R = 1 ,11914.1 ,353.1,341.4,330.8
XS GIS Cut Line= 3
     1879420.897      270385.798      1879858.39      270539.575
     1880509.622      270681.507
#Sta/Elev= 30
       0 2116.34    19.7  2117.4    39.5  2116.3    88.8 2109.42     148 2092.61
   217.1 2067.62   325.6 2038.32   384.8  2017.3   434.1 2014.01     444 2011.12
   463.7  2001.2   483.6 1995.52   528.8 1993.19   548.8  1992.8   553.3 1992.79
     603 1993.54   712.4 2001.68   752.2 2009.56   782.1  2017.5   811.9  2020.3
   861.6 2035.06   881.6 2043.75   911.4 2046.66   931.3 2050.94   961.1 2063.13
  1020.8 2081.88  1040.7 2090.74  1110.4 2110.26  1120.3 2115.84  1130.2 2118.59
#Mann= 3 , 0 , 0
       0     .08       0   528.8    .045       0   548.8     .08       0
Bank Sta=528.8,548.8
XS Rating Curve= 0 ,0
Exp/Cntr=0.3,0.1

Type RM Length L Ch R = 1 ,11572.7 ,283.6,287.6,290.3
XS GIS Cut Line= 3
     1879419.049      271003.842     1879952.582      270874.821
     1880514.804      270763.701
#Sta/Elev= 30
       0 2012.99   129.7  2012.1   179.6 2009.99   209.6 2009.69   259.5 2002.89
   299.4  2001.2   369.3  2001.2   379.2 2002.11   399.2 2007.15   409.2 2007.39
   469.1 1998.82   538.9  1992.5   558.9 1992.63   598.3 1993.93   637.8 1997.51
   687.2 1999.86   766.3  2013.3     786 2014.72   795.9 2016.46   855.2 2033.25
     875 2041.76   884.9 2044.22   914.5 2046.57   924.4 2048.81   944.2 2055.78
     954 2061.93  1023.2 2080.03  1033.1 2084.11  1092.4 2099.88    1122 2110.87
#Mann= 3 , 0 , 0
       0     .08       0   538.9    .045       0   558.9     .08       0
Bank Sta=538.9,558.9
XS Rating Curve= 0 ,0
Exp/Cntr=0.3,0.1

Type RM Length L Ch R = 1 ,11285   ,314.2,302.1,289.9
XS GIS Cut Line= 3
     1879411.131       271183.38     1880342.791      271095.166
     1880543.757      270921.302
#Sta/Elev= 30
       0 2078.87    49.8  2074.1   149.3 2056.08   209.1 2049.53     229 2045.44
   238.9 2046.71   258.8 2043.67   288.7 2038.59   298.7 2035.32   368.4 2020.82
   378.3 2017.54     448 2008.48   497.8 1994.23   544.5 1991.53   557.5 1991.27
   564.5 1991.47   627.2 1997.02   746.7  2000.1   776.5 2003.77   796.4 2009.94
   806.4 2011.58   925.9 2017.83     985  2024.9  1014.6 2030.28  1034.2 2036.17
  1063.8 2040.02    1113 2051.06  1142.5 2061.12  1162.2 2070.27  1201.6 2082.32
#Mann= 3 , 0 , 0
       0      .1       0   544.5    .045       0   564.5      .1       0
Bank Sta=544.5,564.5
XS Rating Curve= 0 ,0
Exp/Cntr=0.3,0.1

Type RM Length L Ch R = 1 ,10982.9 ,332.1,353.2,374.4
XS GIS Cut Line= 3
     1879516.156      271509.447     1880022.436      271372.188
     1880599.045       271028.84
#Sta/Elev= 30
       0 2146.81    39.6 2135.11    59.4 2125.82   118.8 2102.96   138.6 2091.25
   168.2 2079.87     198 2070.24   217.7  2061.8   277.1 2046.62   296.9  2039.2
   366.2 2022.09   376.1 2017.34   415.7 2007.58   425.6 2005.94   475.1 2004.06
   544.3 1998.28   623.2  1997.5   660.5 1990.88   662.7 1990.51   680.5 1991.68
   721.9 1995.23   781.2  2011.1   820.6 2012.37   840.4 2014.83   879.8 2024.63
   919.3  2032.4   978.5 2034.79  1047.6  2040.9  1185.8 2070.14  1195.6 2071.21
#Mann= 3 , 0 , 0
       0      .1       0   660.5    .045       0   680.5      .1       0
Bank Sta=660.5,680.5
XS Rating Curve= 0 ,0
Exp/Cntr=0.3,0.1

Type RM Length L Ch R = 1 ,10629.7 ,297.5,288.2,278.9
XS GIS Cut Line= 3
     1879535.433      271584.081     1880028.627      271539.329
     1880716.099      271789.253
#Sta/Elev= 30
       0 2152.55    19.8 2145.43    39.6 2134.28      99 2112.48   118.8 2100.29
   168.4 2075.03   217.9 2063.53   257.5 2050.27   277.3 2041.77   336.8 2026.49
   346.6 2022.25   425.9 2003.06   495.2 2000.44   633.6 1990.01   689.1 1989.71
   702.8 1989.58   709.1 1989.66   722.6 1991.42     772 2006.29   811.5 2008.28
   841.2    2013   900.5 2028.77   930.2  2038.5     940 2043.88   949.9 2046.91
   989.5    2050  1019.1 2057.45    1029 2061.97  1137.8 2082.75  1226.7 2093.52
#Mann= 3 , 0 , 0
       0      .1       0   689.1    .045       0   709.1      .1       0
Bank Sta=689.1,709.1
XS Rating Curve= 0 ,0
Exp/Cntr=0.3,0.1

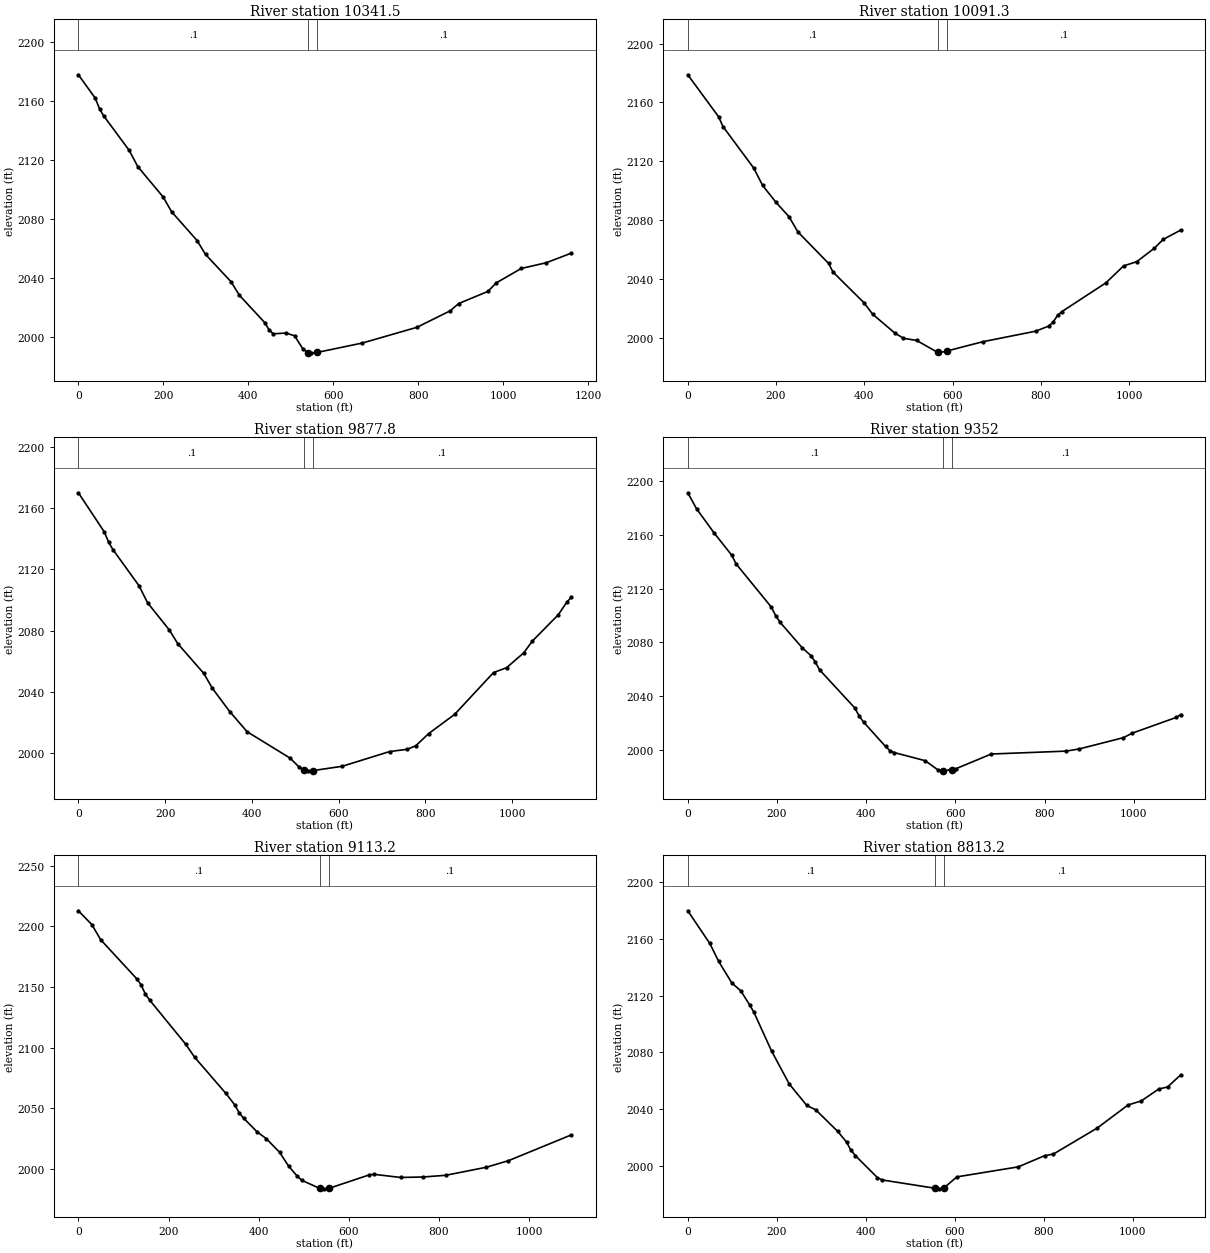
Type RM Length L Ch R = 1 ,10341.5 ,243.1,250.2,257.3
XS GIS Cut Line= 3
     1879517.078      271773.107     1880225.173      271754.447
     1880611.056      271989.868
#Sta/Elev= 30
       0  2177.6    39.9 2161.69    49.9 2154.44    59.9 2149.65   119.7 2126.41
   139.7 2115.49   199.5  2094.9   219.5 2084.87   279.4  2065.4   299.3 2055.99
   359.2 2037.57   379.1 2028.34     439 2009.74     449 2004.85   458.9 2002.28
   488.8 2002.79   508.8 2000.94   528.8 1991.91   541.3 1989.42   548.7  1989.4
   561.3 1989.63   668.4 1996.04   796.8 2006.68   875.4 2017.87     895 2022.75
   963.8 2030.95   983.5 2036.73  1042.4 2046.49  1101.4 2050.39  1160.4 2056.89
#Mann= 3 , 0 , 0
       0      .1       0   541.3    .045       0   561.3      .1       0
Bank Sta=541.3,561.3
XS Rating Curve= 0 ,0
Exp/Cntr=0.3,0.1

Type RM Length L Ch R = 1 ,10091.3 ,217.4,213.4,209.4
XS GIS Cut Line= 2
     1879500.263      271861.152     1880581.241      272143.644
#Sta/Elev= 30
       0 2178.85    69.8 2150.31    79.8 2143.62   149.6 2115.32   169.6 2103.59
   199.5 2092.23   229.4 2082.32   249.4 2072.01   319.2  2050.5   329.2 2044.63
     399 2023.89     419 2015.99   468.9 2003.24   488.8  1999.6   518.7 1998.12
   566.5 1989.98   568.6  1989.7   586.5 1990.89   668.4 1997.25   788.1 2004.41
     818 2007.89     828 2010.56     838 2015.16   847.9 2017.75   947.7 2037.33
   987.6 2048.81  1017.5 2051.71  1057.4 2060.86  1077.4 2066.84  1117.3 2073.23
#Mann= 3 , 0 , 0
       0      .1       0   566.5    .045       0   586.5      .1       0
Bank Sta=566.5,586.5
XS Rating Curve= 0 ,0
Exp/Cntr=0.3,0.1

Type RM Length L Ch R = 1 ,9877.8  ,508,525.9,543.5
XS GIS Cut Line= 2
      1879437.05      272111.357     1880562.552      272268.253
#Sta/Elev= 30
       0 2170.12    59.8 2144.51    69.8 2137.76    79.8 2132.89   139.6 2109.41
   159.5 2098.19   209.3 2080.53   229.3 2071.38   289.1    2052     309 2042.19
   348.9 2027.04   388.8  2013.9   488.4 1996.53   508.4 1990.82   520.7 1988.66
   528.3 1988.28   540.7 1988.44   608.1 1991.25   717.7 2000.91   757.6 2002.34
   777.5  2004.6   807.4 2012.63   867.2 2025.18     957 2052.56   986.9 2055.69
  1026.7 2065.48  1046.7 2073.21  1106.5 2090.41  1126.4 2098.83  1136.4 2101.73
#Mann= 3 , 0 , 0
       0      .1       0   520.7    .045       0   540.7      .1       0
Bank Sta=520.7,540.7
XS Rating Curve= 0 ,0
Exp/Cntr=0.3,0.1

Type RM Length L Ch R = 1 ,9352    ,242.6,238.8,232.9
XS GIS Cut Line= 3
     1879336.827      272250.054     1879725.296       272483.37
     1880154.739      272973.845
#Sta/Elev= 30
       0  2191.3    19.7 2179.38    59.1 2161.39    98.5 2144.88   108.4 2138.34
   187.2 2106.31     197 2099.88   206.9 2094.95   256.1 2076.17   275.8 2070.21
   285.7 2065.47   295.5 2059.57   374.3 2031.25   384.2 2025.24     394 2020.73
   443.3 2002.57   453.2 1999.46     463 1998.03   532.2 1991.99   561.8 1984.89
   571.5 1984.45   591.5 1985.32   601.3 1986.06   680.3 1996.96   848.2 1999.12
   877.9 2000.78   976.6 2009.14   996.4 2012.49  1095.2 2024.22  1105.1 2026.35
#Mann= 3 , 0 , 0
       0      .1       0   571.5    .045       0   591.5      .1       0
Bank Sta=571.5,591.5
XS Rating Curve= 0 ,0
Exp/Cntr=0.3,0.1

Type RM Length L Ch R = 1 ,9113.2  ,301.3,300,298
XS GIS Cut Line= 3
     1879243.955      272413.904     1879660.762      272766.033
     1880106.728      273084.564
#Sta/Elev= 30
       0 2212.88    29.8 2201.52    49.6    2189     129 2157.04   138.9 2152.04
   148.8 2144.06   158.7 2139.04   238.1 2102.95   257.9 2092.22   327.4 2062.37
   347.2 2052.81   357.2 2046.17   367.1 2041.83   396.8 2030.63   416.7  2025.2
   446.4 2013.92   466.3 2002.56   486.1    1994     496 1990.79   535.6 1984.12
   545.6  1983.8   555.6 1984.15   645.3  1995.3   655.2 1995.78     715 1993.17
   764.9 1993.56   814.7 1994.95   904.4 2001.53   954.2 2007.01  1093.7 2028.26
#Mann= 3 , 0 , 0
       0      .1       0   535.6    .045       0   555.6      .1       0
Bank Sta=535.6,555.6
XS Rating Curve= 0 ,0
Exp/Cntr=0.3,0.1

Type RM Length L Ch R = 1 ,8813.2  ,305.4,300.3,304.6
XS GIS Cut Line= 3
     1879076.206      272690.432       1879526.2      273031.752
     1879991.547       273310.96
#Sta/Elev= 30
       0 2179.73    49.5 2156.69    69.4 2144.07    99.1 2128.82   118.9  2123.4
   138.7 2113.57   148.6 2108.19   188.3 2080.88   227.9 2057.72   267.5 2042.56
   287.4 2039.52   336.9 2024.28   356.7 2016.76   366.6    2011   376.5 2007.25
   426.1 1991.75     436 1990.14   554.8 1984.28   564.8 1983.84   574.8 1984.27
   604.3 1992.25   742.4 1999.32   801.6  2007.2   821.3 2008.32     920 2026.71
   989.1 2042.93  1018.7 2045.77  1058.1 2054.15  1077.9 2055.61  1107.5 2064.18
#Mann= 3 , 0 , 0
       0      .1       0   554.8    .045       0   574.8      .1       0
Bank Sta=554.8,574.8
XS Rating Curve= 0 ,0
Exp/Cntr=0.3,0.1