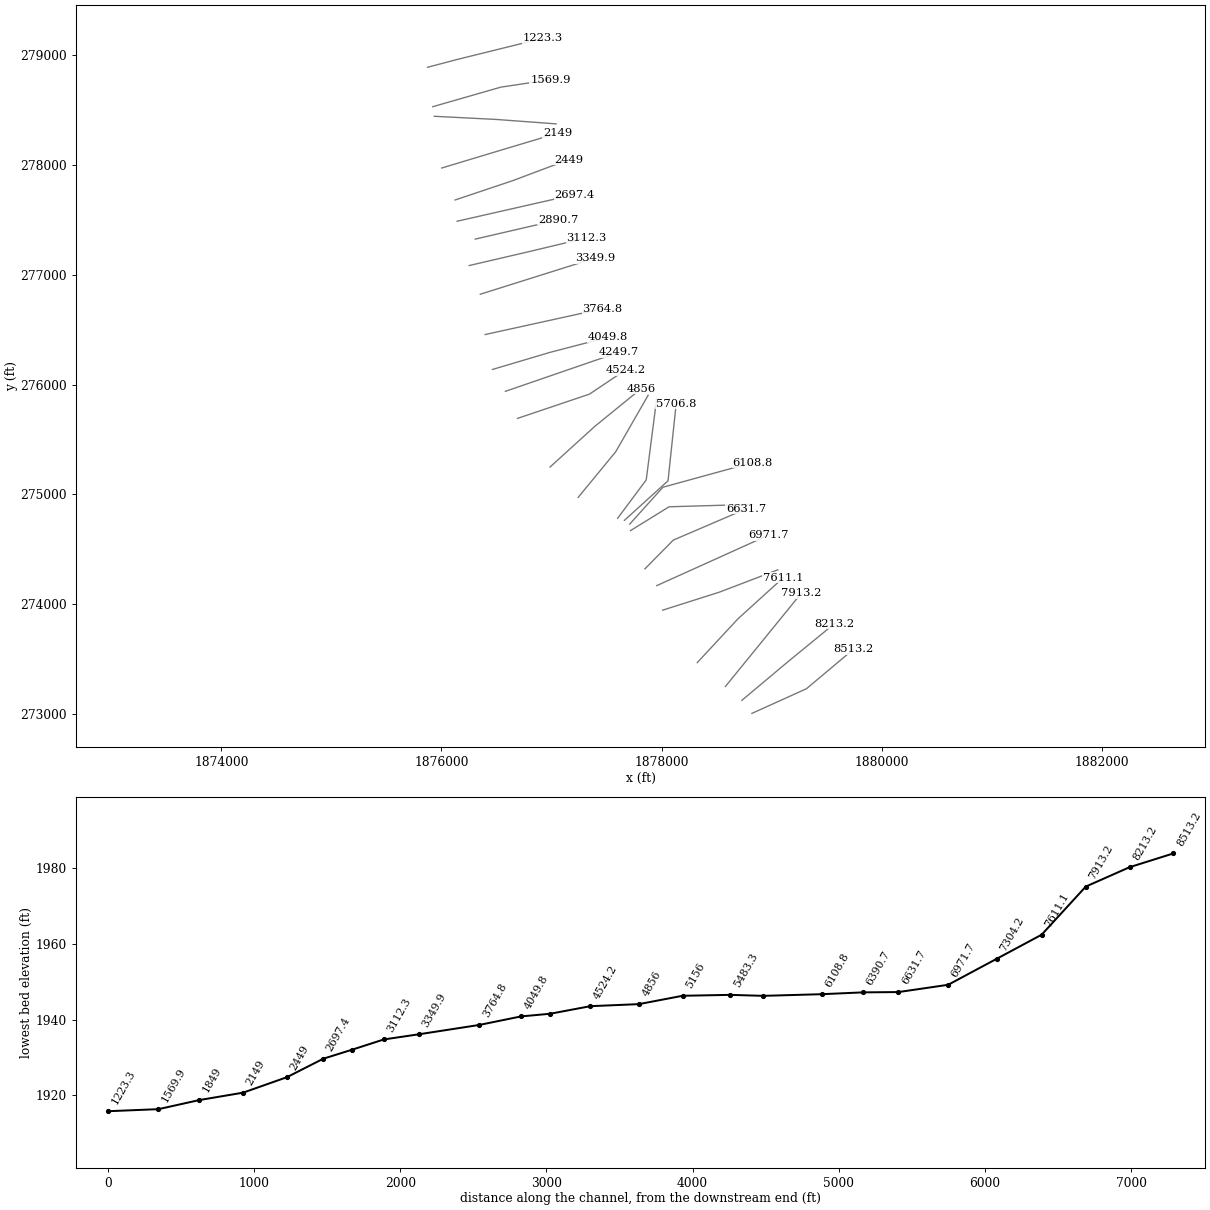
HEC-RAS study SrvyrCrk.prj: SrvyrCrk

--- SrvyrCrk.g01 (geometry) --- (continued)

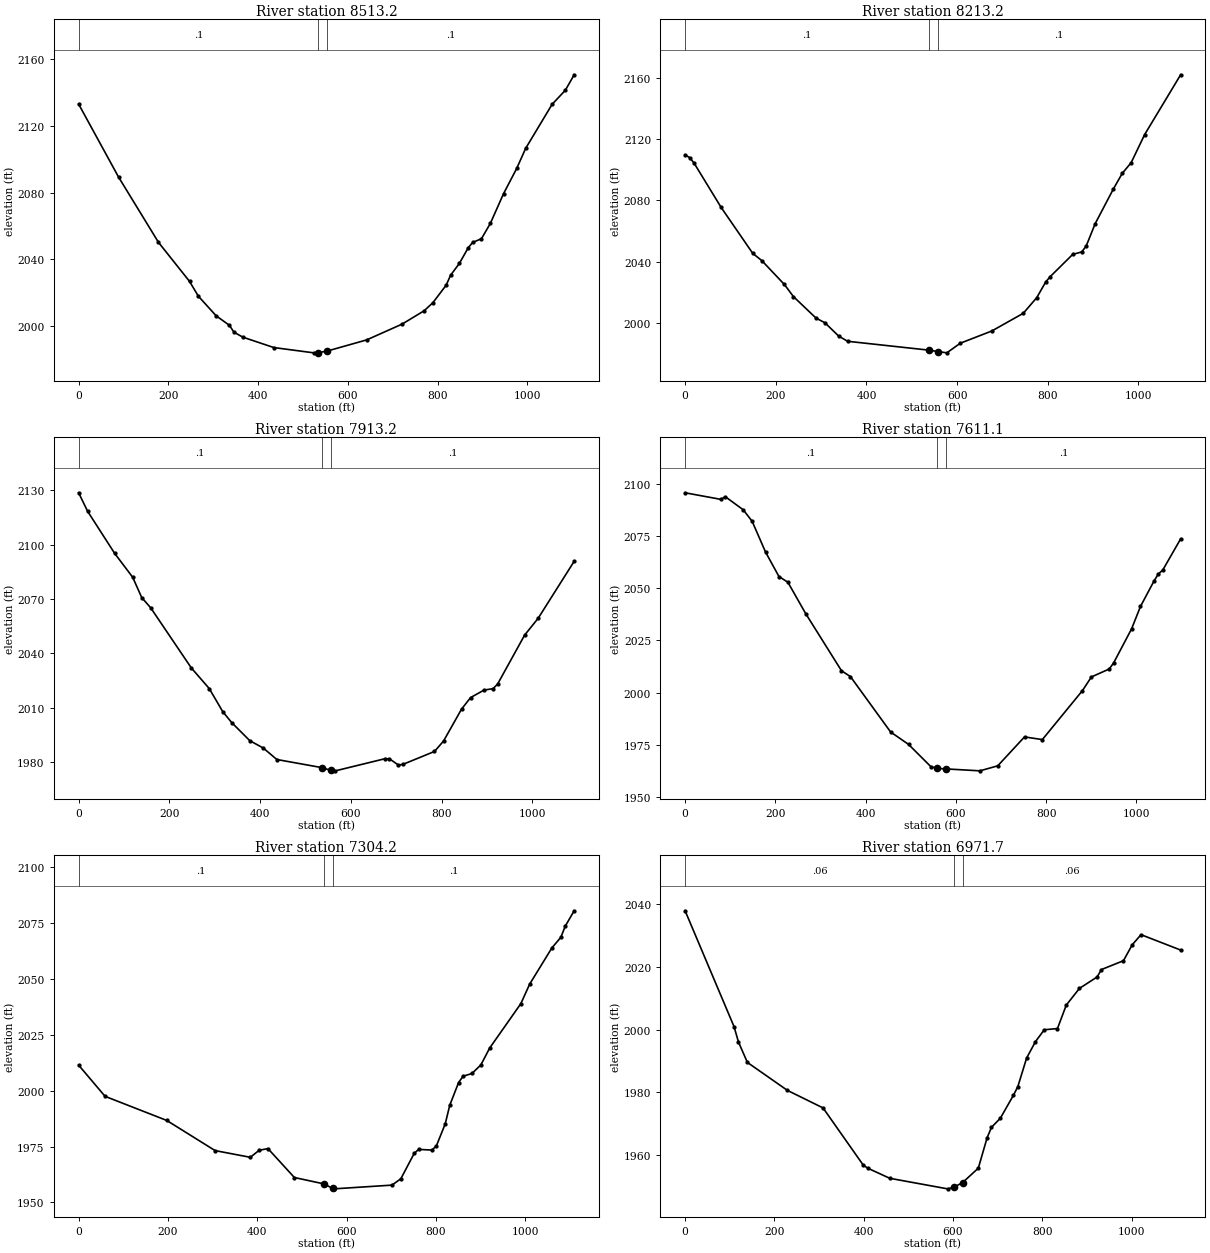
Type RM Length L Ch R = 1 ,8513.2  ,293.1,299.6,299.1
XS GIS Cut Line= 3
     1878821.142      273005.607     1879316.439      273230.002
     1879745.463      273590.919
#Sta/Elev= 30
       0 2133.12      89 2089.35     178 2050.19   247.2 2026.78   266.9  2017.9
   306.5 2006.16   336.1 2000.45     346 1996.38   365.8 1993.37     435 1987.12
     524 1983.95   533.8 1984.04   553.8 1985.01   642.1 1991.72   720.8 2001.17
     770 2009.17   789.6 2014.04   819.2 2024.56     829  2030.5   848.7 2037.63
   868.3 2046.99   878.2 2050.14   897.8 2052.41   917.5 2061.52     947  2079.4
   976.5 2094.63   996.2 2106.53  1055.2 2132.96  1084.7 2141.42  1104.4  2150.7
#Mann= 3 , 0 , 0
       0      .1       0   533.8    .045       0   553.8      .1       0
Bank Sta=533.8,553.8
XS Rating Curve= 0 ,0
Exp/Cntr=0.3,0.1

Type RM Length L Ch R = 1 ,8213.2  ,295.2,300,305
XS GIS Cut Line= 3
       1878729.3      273123.975     1879148.585      273476.113
     1879570.237      273822.155
#Sta/Elev= 30
       0 2109.77      10 2108.09    19.9  2104.4    79.6 2075.41   149.3 2045.36
   169.2 2040.66     219 2025.03   238.9 2017.13   288.7 2003.06   308.6 1999.95
   338.5 1991.34   358.4 1987.87   537.5 1982.08   557.5 1981.18   577.3 1980.31
     607  1986.6   676.5 1994.61   745.9 2006.18   775.6 2016.41   795.5 2026.73
   805.4 2030.19     855 2044.74   874.8 2046.32   884.7  2050.2   904.6 2064.89
   944.2 2087.28   964.1 2097.69   983.9 2104.75  1013.7 2123.16    1093 2162.24
#Mann= 3 , 0 , 0
       0      .1       0   537.5    .045       0   557.5      .1       0
Bank Sta=537.5,557.5
XS Rating Curve= 0 ,0
Exp/Cntr=0.3,0.1

Type RM Length L Ch R = 1 ,7913.2  ,305.7,301.8,297.8
XS GIS Cut Line= 3
     1878580.332      273250.713      1878924.45      273674.622
     1879268.568      274098.531
#Sta/Elev= 30
       0 2128.74    19.8 2118.51    79.4 2095.27   119.1  2082.1     139  2070.9
   158.8 2065.21   248.2 2032.05   287.9  2020.6   317.7 2007.82   337.5 2001.78
   377.2 1991.84     407 1987.76   436.8 1981.44     536 1976.96     556  1975.4
   565.8 1975.18     675 1981.87     685 1981.81   704.8 1978.36   714.8 1978.76
   784.2 1985.89   804.1 1991.62   843.8 2009.25   863.7 2015.63   893.4 2019.78
   913.3 2020.57   923.2 2023.07   982.8 2050.13  1012.6 2059.42    1092  2090.9
#Mann= 3 , 0 , 0
       0      .1       0     536    .045       0     556      .1       0
Bank Sta=536,556
XS Rating Curve= 0 ,0
Exp/Cntr=0.3,0.1

Type RM Length L Ch R = 1 ,7611.1  ,315.9,307,299
XS GIS Cut Line= 3
     1878324.424       273468.01     1878694.611      273867.271
     1879104.116      274239.484
#Sta/Elev= 30
       0 2095.84    79.2 2092.68    89.1 2093.96   128.7  2087.7   148.5 2082.18
   178.2 2067.42   207.9 2055.68   227.7 2052.93   267.3 2037.84   346.5 2010.47
   366.3 2007.67   455.4 1981.08     495 1975.16   544.5 1964.47   558.5 1963.62
   578.5 1963.38   653.2 1962.46   692.7 1964.87     752 1978.73   791.5 1977.45
   880.4 2000.96   900.2  2007.5   939.8 2011.32   949.6  2014.3   989.2 2030.55
  1008.9  2041.3  1038.6  2053.4  1048.4 2056.88  1058.3 2058.78  1097.9 2073.72
#Mann= 3 , 0 , 0
       0      .1       0   558.5    .045       0   578.5      .1       0
Bank Sta=558.5,578.5
XS Rating Curve= 0 ,0
Exp/Cntr=0.3,0.1

Type RM Length L Ch R = 1 ,7304.2  ,332.3,332.4,331.5
XS GIS Cut Line= 3
      1878009.64      273945.278     1878526.282       274109.88
     1879056.148      274312.715
#Sta/Elev= 30
       0 2011.41    59.2 1997.46   197.2 1986.69   305.6  1973.2   384.5  1970.2
   404.2 1973.34   423.9  1974.1   483.1 1961.16   548.6 1958.34   568.6 1956.35
   572.1  1956.1   701.5 1957.76   721.4 1960.57   751.3 1971.92   761.2 1973.73
   791.1 1973.44     801 1975.28   820.9 1985.17   830.9  1993.4   850.8 2003.63
   860.8 2006.44   880.7 2007.68   900.6 2011.47   920.5 2019.09   990.2 2038.91
    1010 2047.65  1059.8 2063.86  1079.7 2068.54  1089.7 2073.58  1109.6 2080.43
#Mann= 3 , 0 , 0
       0      .1       0   548.6    .045       0   568.6      .1       0
Bank Sta=548.6,568.6
XS Rating Curve= 0 ,0
Exp/Cntr=0.3,0.1

Type RM Length L Ch R = 1 ,6971.7  ,339.5,340,340.6
XS GIS Cut Line= 3
     1877956.362      274169.105     1878473.975      274403.206
     1878967.542      274626.838
#Sta/Elev= 30
       0 2037.88   109.6 2000.95   119.6 1996.02   139.5 1989.53   229.2 1980.61
     309 1975.02   398.7 1956.86   408.6 1955.84   458.5 1952.58   587.8 1949.22
   601.7 1949.69   621.7 1951.23   656.8 1955.82   676.5  1965.5   686.3 1968.84
     706  1971.7   735.6 1979.09   745.4 1981.85   765.1 1990.96   784.8 1996.15
   804.5 1999.94   834.1 2000.33   853.8  2007.8   883.4 2013.14   922.8 2016.76
   932.6 2019.14   981.9 2021.96  1001.6 2027.04  1021.3 2030.26    1110 2025.36
#Mann= 3 , 0 , 0
       0     .06       0   601.7    .045       0   621.7     .06       0
Bank Sta=601.7,621.7
XS Rating Curve= 0 ,0
Exp/Cntr=0.3,0.1

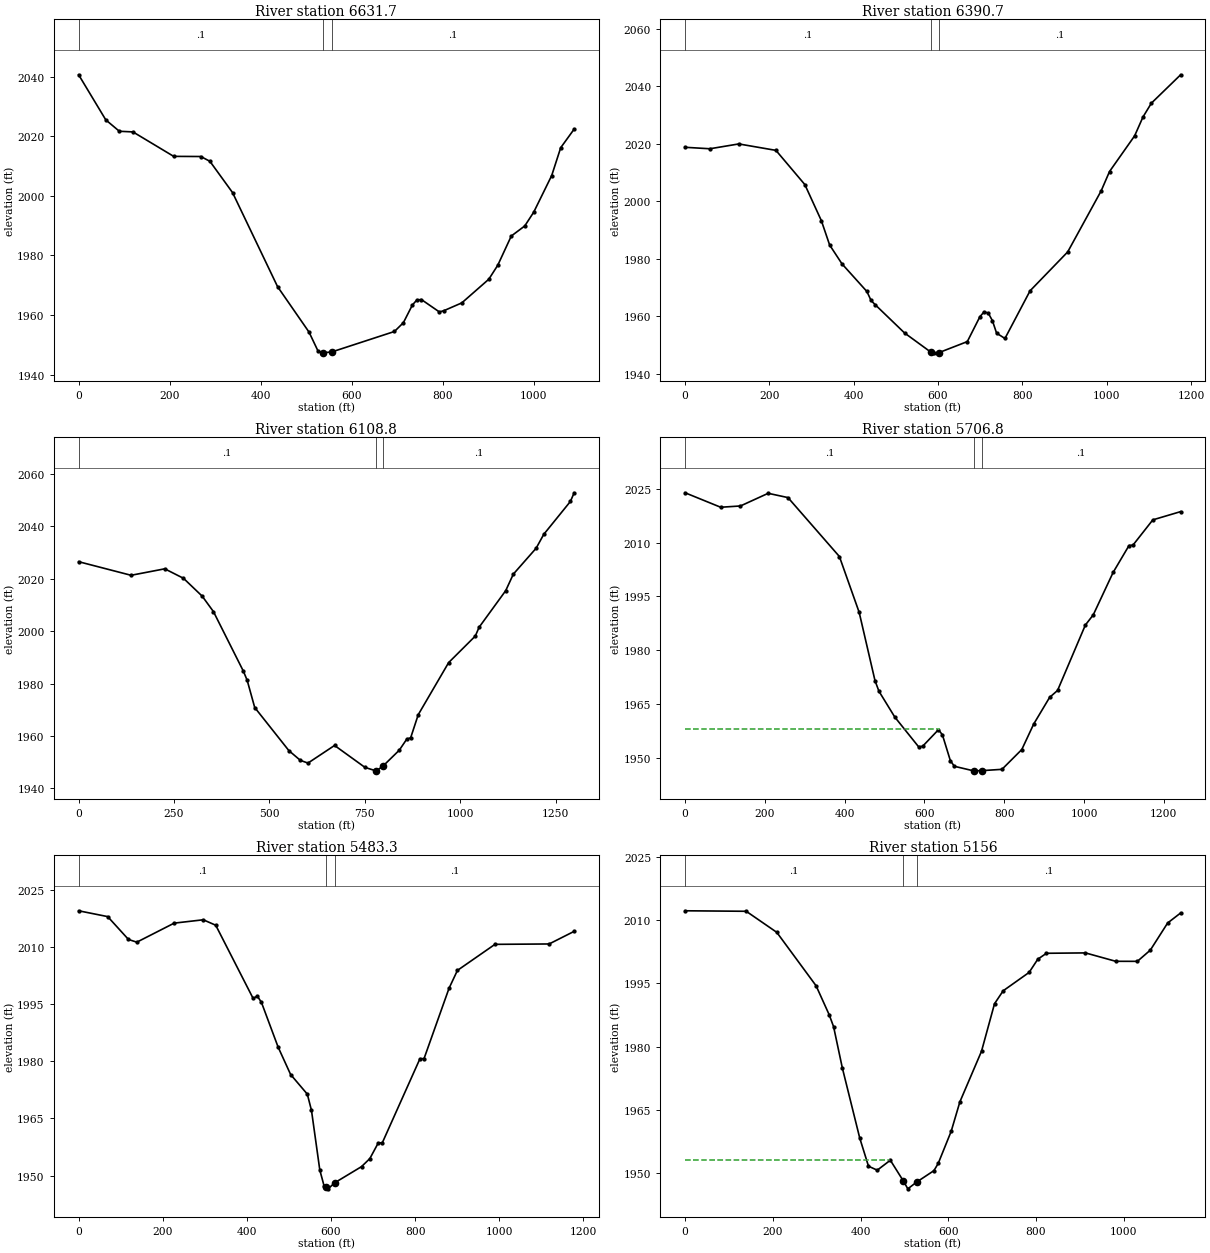
Type RM Length L Ch R = 1 ,6631.7  ,250.6,241,231.4
XS GIS Cut Line= 3
     1877848.162      274321.344     1878106.497      274583.475
     1878768.874      274868.235
#Sta/Elev= 30
       0 2040.68    59.7 2025.53    89.5 2021.71   119.4 2021.49   208.9 2013.28
   268.6 2013.23   288.5 2011.62   338.2 2001.13   437.2 1969.52   506.3 1954.27
   526.1  1947.9   535.9  1947.3   536.9  1947.3   556.9 1947.63     694 1954.47
   713.7 1957.43   733.5 1963.38   743.4 1965.07   753.2  1965.2   792.7 1961.04
   802.6 1961.45   842.1 1964.08   901.4 1972.02   921.1 1976.72   950.8 1986.53
   980.4 1989.91  1000.1 1994.54  1039.6 2006.83  1059.4 2016.19    1089 2022.44
#Mann= 3 , 0 , 0
       0      .1       0   536.9    .045       0   556.9      .1       0
Bank Sta=536.9,556.9
XS Rating Curve= 0 ,0
Exp/Cntr=0.3,0.1

Type RM Length L Ch R = 1 ,6390.7  ,275.6,281.9,288.1
XS GIS Cut Line= 3
     1877718.065      274670.049     1878067.807      274886.806
     1878831.643      274908.972
#Sta/Elev= 30
       0 2018.76    58.8 2018.25   127.4 2019.93   215.5 2017.69   284.1 2005.78
   323.3 1993.21   342.9 1984.75   372.3 1978.17   431.3 1968.57   441.2 1965.44
   451.2 1963.94   520.6 1954.14   582.3 1947.54   590.1 1947.22   602.3  1947.3
   669.5 1951.13   699.3 1959.77   709.2 1961.47   719.1 1961.08     729 1958.44
     739 1954.06   758.8 1952.22   818.4 1968.81   907.7 1982.35   987.1 2003.61
  1006.9 2010.33  1066.5 2022.76  1086.3 2029.32  1106.2 2034.12  1175.6    2044
#Mann= 3 , 0 , 0
       0      .1       0   582.3    .045       0   602.3      .1       0
Bank Sta=582.3,602.3
XS Rating Curve= 0 ,0
Exp/Cntr=0.3,0.1

Type RM Length L Ch R = 1 ,6108.8  ,347.3,402,435
XS GIS Cut Line= 3
     1877710.448      274729.094     1878012.093      275064.781
     1878828.637      275289.565
#Sta/Elev= 30
       0 2026.56   137.4 2021.37   225.6 2023.84   274.7 2020.22   323.8 2013.39
   353.2  2007.5   431.7 1984.74   441.5 1981.31   461.3 1970.91   550.9 1954.44
   580.8 1950.75   600.8  1949.7   670.5 1956.43   750.2 1948.05     778 1946.77
   780.1 1946.74     798 1948.65   839.9  1954.6   859.8 1958.87   869.8 1959.34
   889.7 1968.17   969.4 1988.06  1039.2 1998.18  1049.1 2001.53  1118.9 2015.52
  1138.8 2021.81  1198.6 2031.71  1218.5 2036.99  1288.3 2049.55  1298.2 2052.86
#Mann= 3 , 0 , 0
       0      .1       0     778    .045       0     798      .1       0
#XS Ineff= 2 , 0
          671.22  1956.2
Permanent Ineff=
       F       F
Bank Sta=778,798
XS Rating Curve= 0 ,0
Exp/Cntr=0.3,0.1

Type RM Length L Ch R = 1 ,5706.8  ,248.7,223.5,219.6
XS GIS Cut Line= 3
     1877662.424      274763.305     1878058.522       275123.59
     1878132.807      275826.204
#Sta/Elev= 30
       0 2023.92    89.2 2019.88   138.8 2020.24   208.2 2023.77   257.8 2022.58
   386.7 2006.13   436.3 1990.54     476 1971.46   485.9 1968.51   525.5 1961.32
   585.2 1953.02   595.2 1953.14     635 1957.78   644.9 1956.36   664.8 1949.16
   674.8 1947.57     723  1946.3     743 1946.35   794.2 1946.72   843.9 1952.25
   873.8 1959.38   913.6  1966.8   933.5 1968.74  1003.2    1987    1023 1989.84
  1072.8 2001.69  1112.6 2009.19  1122.6 2009.32  1172.3 2016.36    1242 2018.66
#Mann= 3 , 0 , 0
       0      .1       0     723    .045       0     743      .1       0
#XS Ineff= 2 , 0
          636.46  1958.1
Permanent Ineff=
       F       F
Bank Sta=723,743
XS Rating Curve= 0 ,0
Exp/Cntr=0.3,0.1

Type RM Length L Ch R = 1 ,5483.3  ,342.2,327.2,316.1
XS GIS Cut Line= 3
     1877601.064      274782.685     1877860.428      275131.328
     1877955.143      275868.606
#Sta/Elev= 30
       0 2019.45    69.1 2017.92   118.5 2011.93   138.3 2011.22   227.1 2016.21
   296.3 2017.09   325.9 2015.66   414.8 1996.47   424.7  1997.1   434.5 1995.45
   474.2 1983.71   503.9 1976.53   543.6 1971.38   553.5 1967.11   573.3 1951.47
   583.2 1947.42   588.7 1946.94   593.1 1946.56   608.7 1948.15   672.4 1952.38
   692.2 1954.49     712 1958.55     722 1958.67   811.2 1980.64   821.1 1980.72
   880.5 1999.15   900.4 2003.82   989.6 2010.65  1118.4 2010.75  1177.9 2014.06
#Mann= 3 , 0 , 0
       0      .1       0   588.7    .045       0   608.7      .1       0
Bank Sta=588.7,608.7
XS Rating Curve= 0 ,0
Exp/Cntr=0.3,0.1

Type RM Length L Ch R = 1 ,5156    ,303.6,299.7,290.5
XS GIS Cut Line= 3
     1877242.124      274972.373      1877583.26       275388.05
     1877877.709      275901.972
#Sta/Elev= 30
       0  2012.2   139.4 2012.08   209.1 2007.09   298.7 1994.43   328.6 1987.56
   338.6 1984.74   358.5 1974.99   398.3 1958.33   418.2 1951.68   438.2 1950.74
     468  1953.1   497.9 1948.15   507.9 1946.32   527.7  1947.9   567.4 1950.63
   577.2 1952.34   606.8 1959.96   626.6 1966.93   675.9 1978.91   705.6 1990.18
   725.3 1993.24   784.5  1997.6   804.3 2000.73     824 2002.13   912.9 2002.22
     982 2000.23  1031.3 2000.22  1060.9 2002.88  1100.4 2009.31    1130 2011.68
#Mann= 3 , 0 , 0
       0      .1       0   497.9    .045       0   527.7      .1       0
#XS Ineff= 2 , 0
           468.1  1953.1
Permanent Ineff=
       F       F
Bank Sta=497.9,527.7
XS Rating Curve= 0 ,0
Exp/Cntr=0.3,0.1

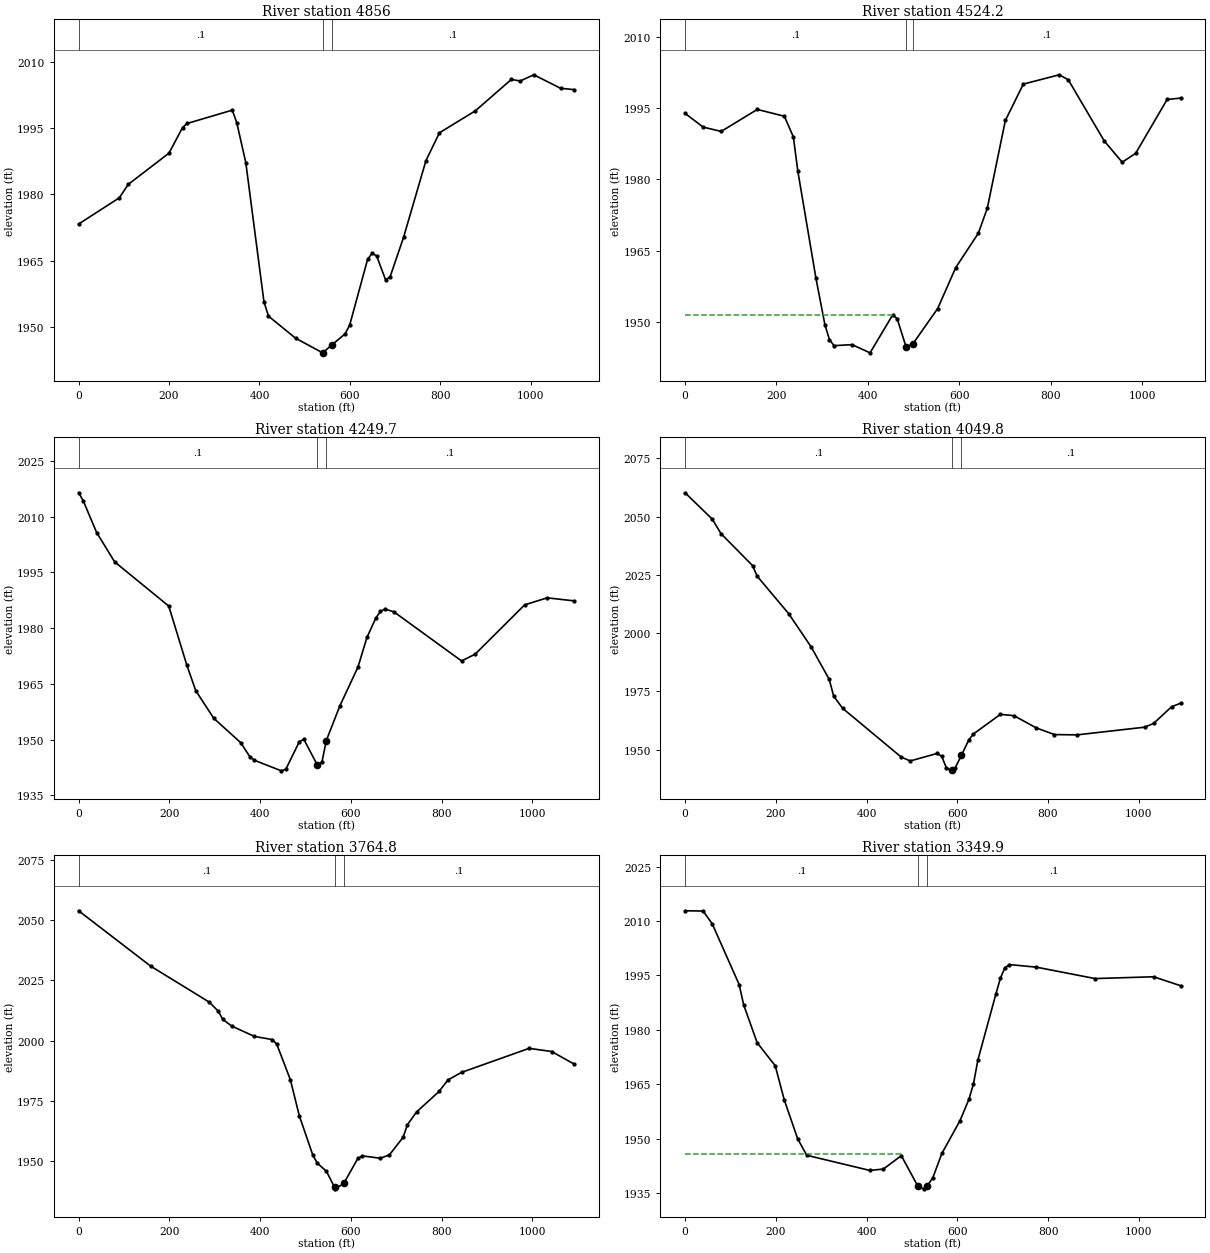
Type RM Length L Ch R = 1 ,4856    ,342.7,331.5,321.8
XS GIS Cut Line= 3
     1876986.086      275248.474     1877392.556      275618.515
     1877816.041      275963.694
#Sta/Elev= 30
       0 1973.28      90 1979.22   109.9 1982.27   199.9 1989.34   229.9 1995.14
   239.9 1996.05   339.8 1999.07   349.8 1996.22   369.8 1987.15   409.8 1955.72
   419.8 1952.44   479.7 1947.43   539.7 1944.11   559.7 1945.87   589.4 1948.41
   599.4 1950.37   639.1 1965.27     649 1966.63     659 1966.09   678.8 1960.66
   688.8  1961.3   718.6 1970.25   768.2 1987.65     798 1993.94   877.5 1998.92
     957 2006.02   976.8 2005.68  1006.6 2007.08  1066.2 2004.01    1096 2003.72
#Mann= 3 , 0 , 0
       0      .1       0   539.7    .045       0   559.7      .1       0
Bank Sta=539.7,559.7
XS Rating Curve= 0 ,0
Exp/Cntr=0.3,0.1

Type RM Length L Ch R = 1 ,4524.2  ,273.9,274.6,275.4
XS GIS Cut Line= 3
     1876690.436      275691.562     1877345.074       275912.87
     1877671.666      276132.293
#Sta/Elev= 30
       0 1993.87    39.5 1990.99      79 1990.08     158  1994.7   217.2 1993.27
   236.9 1988.94   246.8 1981.69   286.3 1959.27     306 1949.47   315.9 1946.36
   325.8 1945.08   365.3 1945.29   404.8 1943.57   454.1 1951.51     464 1950.78
   483.7 1944.79   498.6 1945.47   552.8 1952.88   592.3 1961.48   641.7 1968.68
   661.4 1973.96   700.9 1992.38   740.2 2000.02   818.9 2001.98   838.6 2000.93
   917.3 1988.08   956.6 1983.61   986.1 1985.49    1055  1996.8  1084.5 1997.08
#Mann= 3 , 0 , 0
       0      .1       0   483.7    .045       0   498.6      .1       0
#XS Ineff= 2 , 0
          454.13 1951.52
Permanent Ineff=
       F       F
Bank Sta=483.7,498.6
XS Rating Curve= 0 ,0
Exp/Cntr=0.3,0.1

Type RM Length L Ch R = 1 ,4249.7  ,201.7,199.8,197.9
XS GIS Cut Line= 3
     1876580.502      275938.117     1877096.678      276116.101
     1877612.853      276294.086
#Sta/Elev= 30
       0 2016.45     9.9 2014.36    39.7 2005.75    79.4 1997.84   198.6 1985.94
   238.2 1970.12   258.1 1963.15   297.8 1955.72   357.4 1949.13   377.2 1945.39
   387.2 1944.42   446.7 1941.57   456.6    1942   486.4 1949.43   496.4 1950.03
   525.8 1943.18   536.1 1943.89   545.8 1949.74   575.8 1959.11   615.5 1969.49
   635.4 1977.51   655.2 1982.78   665.1 1984.49     675 1985.14   694.9 1984.38
   843.8 1971.17   873.6 1972.97   982.8 1986.26  1032.4 1988.16    1092 1987.34
#Mann= 3 , 0 , 0
       0      .1       0   525.8    .045       0   545.8      .1       0
Bank Sta=525.8,545.8
XS Rating Curve= 0 ,0
Exp/Cntr=0.3,0.1

Type RM Length L Ch R = 1 ,4049.8  ,285.9,285,284.1
XS GIS Cut Line= 3
     1876462.881      276137.206     1876986.134      276292.922
     1877514.843      276430.782
#Sta/Elev= 30
       0 2060.24    59.6 2048.97    79.4 2042.64   148.9 2028.93   158.8 2024.44
   228.3 2008.34   277.9 1994.04   317.6 1980.16   327.6  1972.9   347.4 1967.68
   476.4 1946.76   496.3 1945.11   555.9 1948.34   565.8 1947.04   575.7 1942.22
   585.7 1940.86     589 1941.33   595.6 1942.26     609 1947.48   625.4 1954.16
   635.3 1956.65     695 1965.11   724.8 1964.55   774.4 1959.26   814.2 1956.43
   863.8  1956.3  1012.8  1959.6  1032.7 1961.21  1072.4 1968.38  1092.3 1969.89
#Mann= 3 , 0 , 0
       0      .1       0     589    .045       0     609      .1       0
Bank Sta=589,609
XS Rating Curve= 0 ,0
Exp/Cntr=0.3,0.1

Type RM Length L Ch R = 1 ,3764.8  ,412.6,414.8,417.1
XS GIS Cut Line= 3
     1876397.524      276455.486      1876930.78       276572.76
     1877464.037      276690.034
#Sta/Elev= 30
       0  2053.8   158.8 2030.86   287.9 2015.95   307.8  2012.2   317.7 2008.79
   337.5 2006.04   387.2 2001.76   426.9 2000.44   436.8 1998.46   466.6  1983.8
   486.4 1968.82   516.2 1952.51   526.2 1949.21     546 1945.91   564.2 1939.18
   565.8 1938.61   584.2 1940.83   615.5 1951.28   625.4 1952.26   665.1 1951.28
     685  1952.7   714.8 1959.91   724.7 1965.23   744.6 1970.44   794.2 1978.95
     814 1983.75   843.8 1986.85   992.7 1996.81  1042.4  1995.5    1092 1990.27
#Mann= 3 , 0 , 0
       0      .1       0   564.2    .045       0   584.2      .1       0
Bank Sta=564.2,584.2
XS Rating Curve= 0 ,0
Exp/Cntr=0.3,0.1

Type RM Length L Ch R = 1 ,3349.9  ,239.4,237.6,235.8
XS GIS Cut Line= 3
     1876352.526      276822.317     1876873.258      276986.492
     1877393.991      277150.667
#Sta/Elev= 30
       0 2012.84    39.7 2012.77    59.6 2009.28   119.1  1992.5     129 1986.93
   158.8 1976.44   198.6 1970.09   218.4 1960.72   248.2 1949.89     268 1945.39
     407 1941.21   436.8 1941.58   476.5 1945.28   513.3 1936.78   526.2 1936.13
   533.3 1936.88     546 1939.22   565.8 1945.89   605.6 1954.89   625.4  1960.8
   635.4 1965.06   645.3 1971.72     685 1989.92   694.9 1994.29   704.8 1997.12
   714.8    1998   774.3 1997.28   903.4 1994.14  1032.4 1994.63    1092 1992.17
#Mann= 3 , 0 , 0
       0      .1       0   513.3    .045       0   533.3      .1       0
#XS Ineff= 2 , 0
          474.79 1945.77
Permanent Ineff=
       F       F
Bank Sta=513.3,533.3
XS Rating Curve= 0 ,0
Exp/Cntr=0.3,0.1

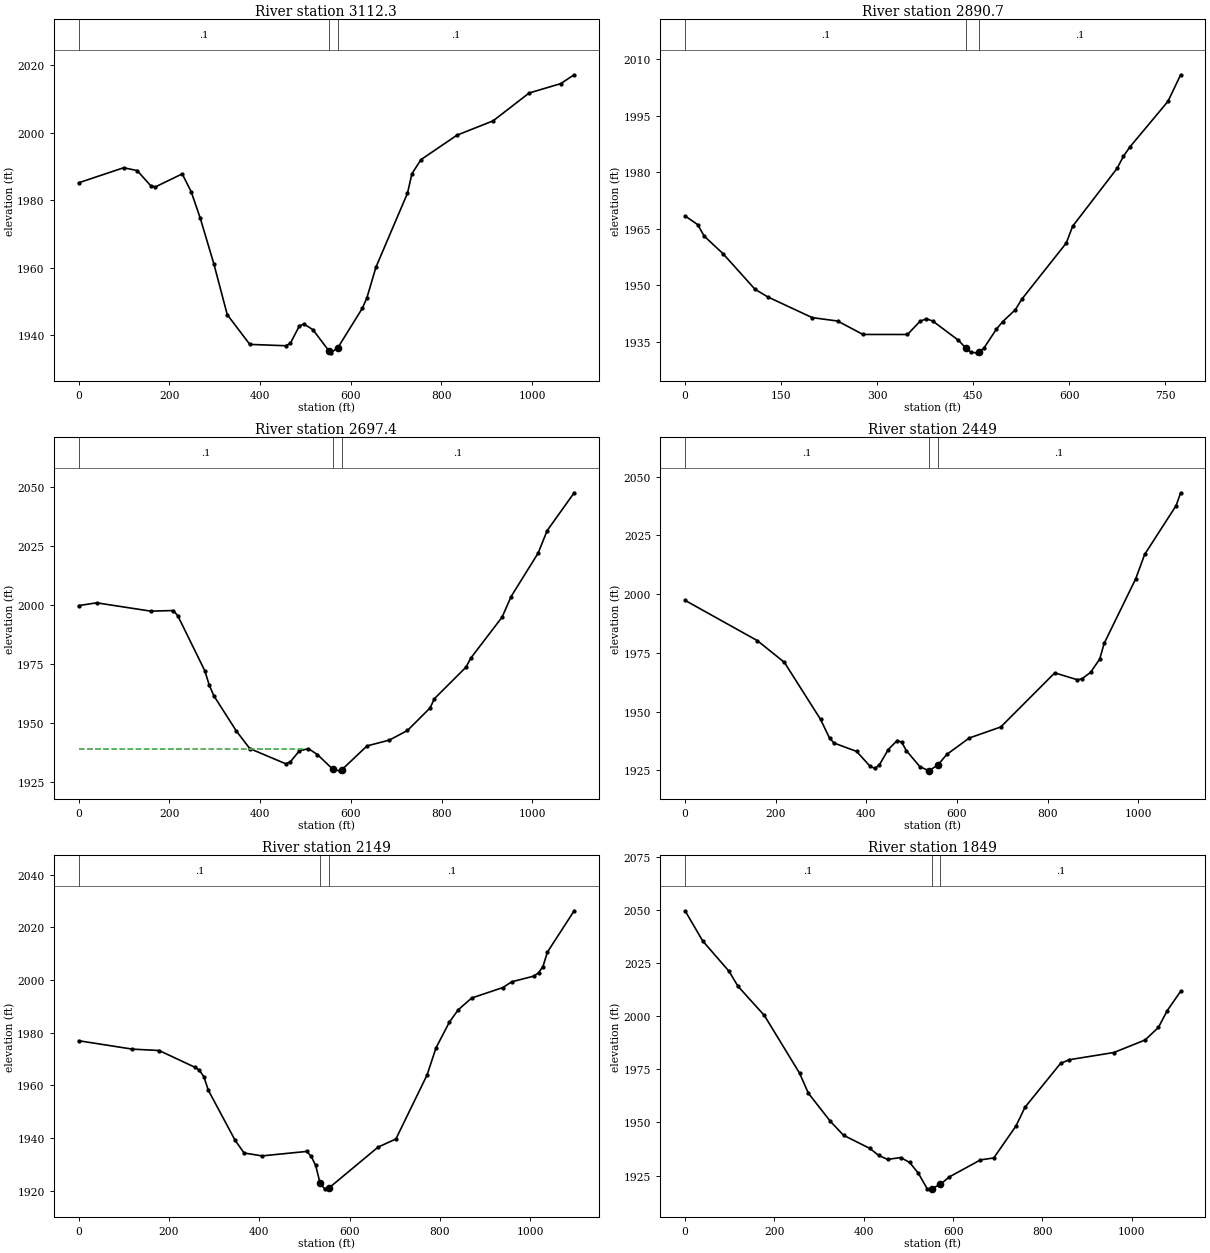
Type RM Length L Ch R = 1 ,3112.3  ,221.6,221.5,221.3
XS GIS Cut Line= 3
     1876251.978      277083.596     1876783.942      277207.633
     1877315.349      277334.603
#Sta/Elev= 30
       0 1985.14    99.3  1989.6   129.1 1988.76   158.9 1984.28   168.8  1983.9
   228.4 1987.78   248.3 1982.45   268.2 1974.64     298  1961.2   327.7 1946.08
   377.4 1937.28   456.8 1936.88   466.8  1937.6   486.6 1942.74   496.6 1943.33
   516.4 1941.66   551.8 1935.38   556.2 1934.78   571.8 1936.36   625.7 1948.02
   635.6 1951.06   655.5 1960.14     725 1982.04     735 1987.86   754.8    1992
   834.3 1999.25   913.8 2003.48   993.3 2011.73  1062.8  2014.5  1092.6 2017.13
#Mann= 3 , 0 , 0
       0      .1       0   551.8    .045       0   571.8      .1       0
#XS Ineff= 2 , 0
           496.2 1943.16
Permanent Ineff=
       F       F
Bank Sta=551.8,571.8
XS Rating Curve= 0 ,0
Exp/Cntr=0.3,0.1

Type RM Length L Ch R = 1 ,2890.7  ,193.4,193.3,193.2
XS GIS Cut Line= 2
     1876306.629      277324.289     1877060.314      277499.169
#Sta/Elev= 30
       0 1968.36    19.8 1966.03    29.8    1963    59.5 1958.29   109.1  1948.9
     129 1946.87   198.4 1941.37   238.1 1940.46   277.7  1936.9   347.2 1936.89
     367 1940.42   376.9 1941.06   386.8 1940.44   426.5 1935.39   438.5 1933.28
   446.4 1932.15   456.3 1932.02   458.5 1932.28   466.2 1933.18     486  1938.3
     496 1940.32   515.8 1943.49   525.7 1946.26   595.2 1961.18   605.1 1965.62
   674.5 1980.99   684.4  1984.2   694.4 1986.65   753.9 1998.76   773.7 2005.82
#Mann= 3 , 0 , 0
       0      .1       0   438.5    .045       0   458.5      .1       0
#XS Ineff= 2 , 0
          377.35  1940.8
Permanent Ineff=
       F       F
Bank Sta=438.5,458.5
XS Rating Curve= 0 ,0
Exp/Cntr=0.3,0.1

Type RM Length L Ch R = 1 ,2697.4  ,245.7,248.3,251.7
XS GIS Cut Line= 3
     1876142.377      277487.115      1876674.77       277608.25
     1877207.163      277729.385
#Sta/Elev= 30
       0 1999.75    39.7 2000.93   158.8 1997.41   208.5 1997.66   218.4 1995.48
     278 1972.14   287.9 1965.99   297.8 1961.57   347.4 1946.61   377.2 1939.11
   456.6 1932.66   466.6 1933.52   486.4 1938.15   506.3 1939.09   526.2  1936.6
   560.3 1930.32   575.8 1929.68   580.3 1930.19   635.4 1940.24     685 1942.74
   724.7  1946.8   774.3 1956.33   784.2 1960.32   853.8 1973.68   863.7 1977.37
   933.2 1994.87     953 2003.59  1012.6 2022.02  1032.4 2031.54    1092  2047.6
#Mann= 3 , 0 , 0
       0      .1       0   560.3    .045       0   580.3      .1       0
#XS Ineff= 2 , 0
          497.13 1939.11
Permanent Ineff=
       F       F
Bank Sta=560.3,580.3
XS Rating Curve= 0 ,0
Exp/Cntr=0.3,0.1

Type RM Length L Ch R = 1 ,2449    ,300.7,299.9,298.2
XS GIS Cut Line= 3
     1876124.061       277680.66     1876643.325      277855.133
     1877154.056      278047.291
#Sta/Elev= 30
       0 1997.37   159.4 1980.24   219.1 1970.98   298.8 1946.74   318.7 1938.75
   328.7 1936.62   378.5 1933.07   408.4  1926.7   418.3 1925.87   428.3 1927.19
   448.2 1933.85   468.1 1937.71   478.1 1936.96     488 1933.45   517.9 1926.63
   537.8  1924.8   557.8 1927.29   577.6 1931.81   627.2 1938.79   696.6 1943.47
   815.7  1966.5   865.3  1963.6   875.2 1963.89     895 1966.77   914.9  1972.4
   924.8 1979.09   994.3 2006.53  1014.1 2016.94  1083.6 2037.74  1093.5 2043.18
#Mann= 3 , 0 , 0
       0      .1       0   537.8    .045       0   557.8      .1       0
#XS Ineff= 2 , 0
           469.2 1937.18
Permanent Ineff=
       F       F
Bank Sta=537.8,557.8
XS Rating Curve= 0 ,0
Exp/Cntr=0.3,0.1

Type RM Length L Ch R = 1 ,2149    ,307.6,299.8,291.4
XS GIS Cut Line= 3
     1876002.494      277971.759     1876524.053       278129.29
     1877053.318      278288.291
#Sta/Elev= 30
       0 1976.97   118.9 1973.78   178.3 1973.25   257.6 1966.88   267.5 1965.75
   277.4 1963.28   287.3 1958.14   346.7 1939.11   366.5 1934.32   406.2 1933.23
   505.2 1934.92   515.1 1933.06     525 1929.58   534.8 1922.83   544.8 1920.71
   554.8 1921.09   663.2 1936.56   702.7 1939.65   771.8 1963.99   791.5 1974.25
   821.2 1984.07   840.9 1988.76   870.5 1993.19   939.6 1997.17   959.3 1999.36
  1008.6 2001.53  1018.5  2002.8  1028.4 2005.16  1038.2 2010.63  1097.5 2026.33
#Mann= 3 , 0 , 0
       0      .1       0   534.8    .045       0   554.8      .1       0
Bank Sta=534.8,554.8
XS Rating Curve= 0 ,0
Exp/Cntr=0.3,0.1

Type RM Length L Ch R = 1 ,1849    ,271.6,279.2,287.6
XS GIS Cut Line= 3
     1875934.471      278442.627     1876495.354      278414.091
     1877041.499      278373.549
#Sta/Elev= 30
       0 2049.73    39.4 2035.52    98.5  2021.2   118.2 2014.22   177.4 2000.42
   256.2 1973.25   275.9 1963.81   325.1 1950.57   354.7 1943.98   413.8 1937.76
   433.5 1934.47   453.2 1932.64   482.8 1933.47   502.5  1931.2   522.2  1926.1
   541.9  1918.8   551.6 1918.75   571.6 1920.92   591.5 1924.37   661.2 1932.38
     691 1933.31   740.8 1948.38   760.8 1957.16   840.4 1977.82   860.3 1979.58
   959.9 1982.97  1029.6 1988.85  1059.5 1994.77  1079.4 2002.73  1109.3  2011.8
#Mann= 3 , 0 , 0
       0      .1       0   551.6    .045       0   571.6      .1       0
Bank Sta=551.6,571.6
XS Rating Curve= 0 ,0
Exp/Cntr=0.3,0.1

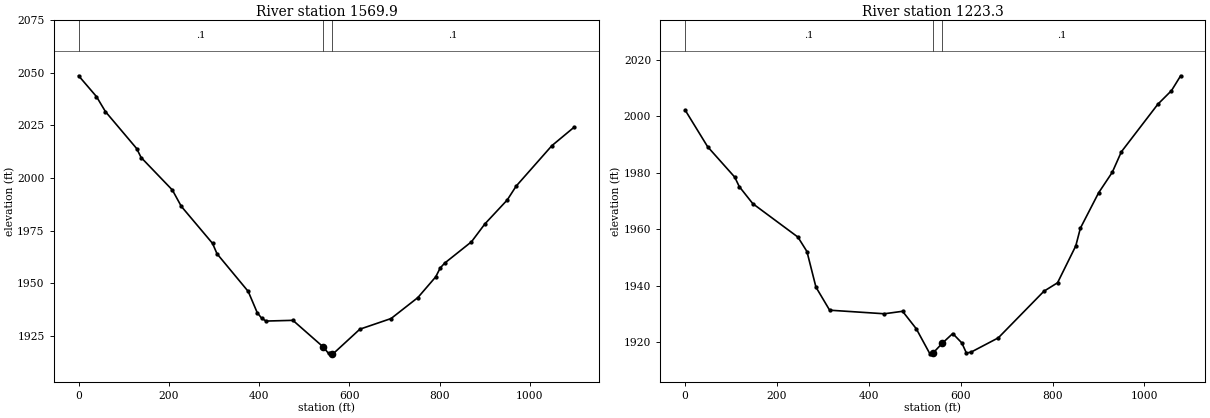
Type RM Length L Ch R = 1 ,1569.9  ,347.5,346.5,345.5
XS GIS Cut Line= 3
     1875920.803      278530.008      1876538.77      278707.851
     1876988.968      278775.624
#Sta/Elev= 30
       0 2048.58    39.6 2038.67    59.4 2031.55   128.6 2013.98   138.5 2009.71
   207.8 1994.24   227.5 1986.51   296.8 1968.87   306.7 1963.94   375.9 1946.02
   395.7 1935.99   405.6 1933.27   415.5 1931.94   474.9 1932.28   541.9 1919.66
     554 1916.52   561.9 1916.38   563.9 1916.35   623.3 1928.07   692.5 1933.14
   751.9 1943.11   791.5 1952.98   801.4 1957.19   811.3 1959.49   870.7 1969.64
   900.4 1978.13   949.9 1989.51   969.7  1996.1  1048.8 2015.33  1098.3 2024.15
#Mann= 3 , 0 , 0
       0      .1       0   541.9    .045       0   561.9      .1       0
Bank Sta=541.9,561.9
XS Rating Curve= 0 ,0
Exp/Cntr=0.3,0.1

Type RM Length L Ch R = 1 ,1223.3  ,153.3,155,156.6
XS GIS Cut Line= 3
     1875873.299      278888.921     1876148.773      278961.658
     1876919.472      279152.502
#Sta/Elev= 30
       0 2002.27    49.1 1989.24   108.1 1978.46   117.9 1975.12   147.4 1969.06
   245.6 1957.21   265.3 1952.08   284.9 1939.45   314.7 1931.28   433.8 1930.01
   473.5 1930.89   503.3  1924.7     533  1915.8   540.3 1916.17   560.3 1919.61
   582.7    1923   602.5 1919.67   612.4  1916.1   622.4 1916.39   681.9 1921.47
   781.2    1938   810.9    1941   850.6 1954.08   860.6 1960.36   900.2 1972.88
     930 1980.17   949.9 1987.46  1029.3 2004.33    1059 2009.15  1078.9 2014.41
#Mann= 3 , 0 , 0
       0      .1       0   540.3    .045       0   560.3      .1       0
#XS Ineff= 2 , 0
                          583.71         1922.82
Permanent Ineff=
       F       F
Bank Sta=540.3,560.3
XS Rating Curve= 0 ,0
Exp/Cntr=0.3,0.1