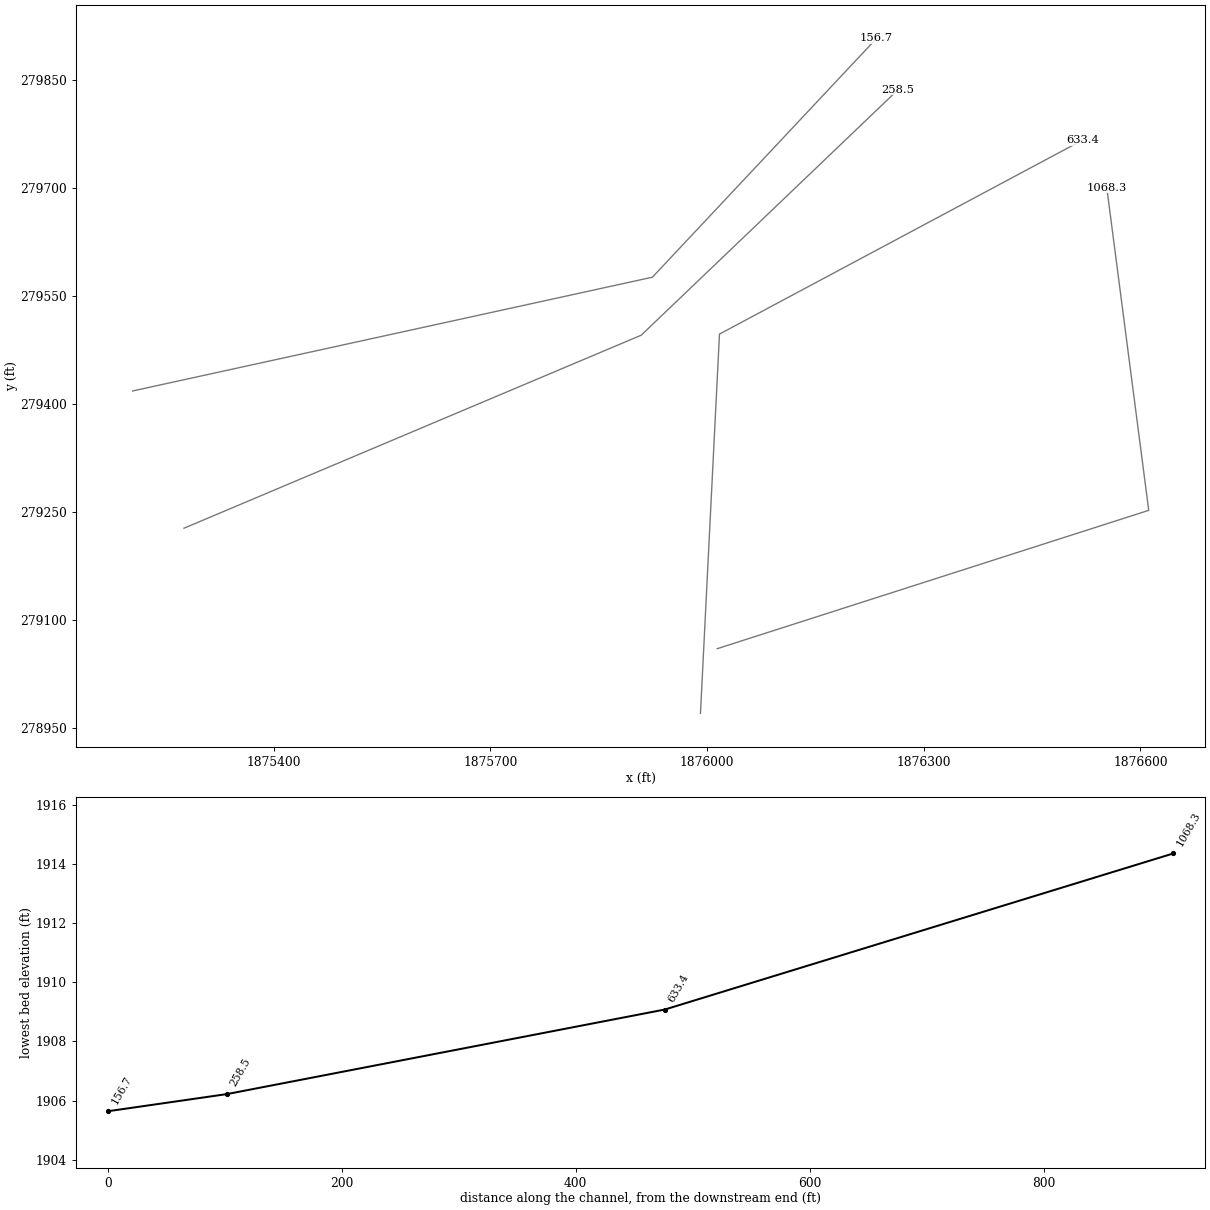
HEC-RAS study SrvyrCrk.prj: SrvyrCrk

--- SrvyrCrk.g01 (geometry) --- (continued)

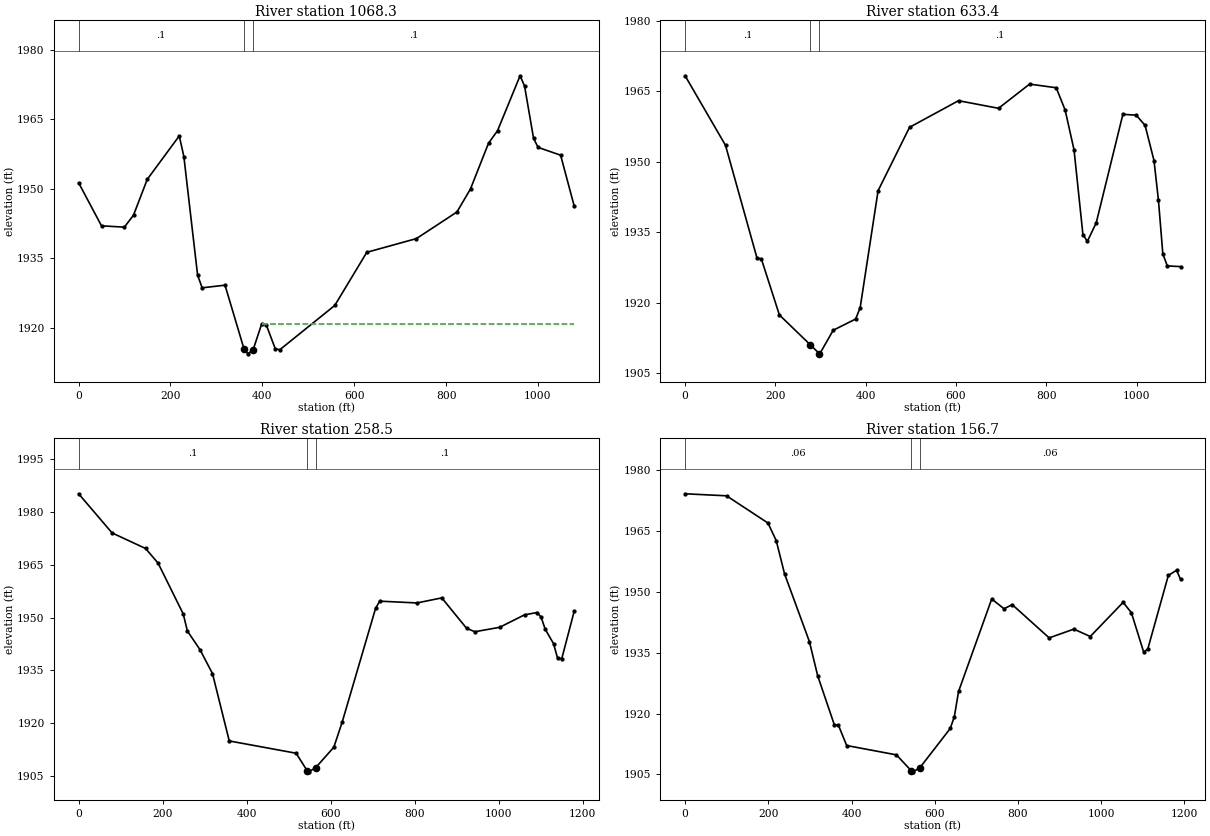
Type RM Length L Ch R = 1 ,1068.3  ,403.7,434.9,465
XS GIS Cut Line= 3
     1876014.131      279060.705     1876611.508      279252.609
     1876553.433      279700.276
#Sta/Elev= 30
       0 1951.25    49.8 1941.97    99.6 1941.69   119.5 1944.28   149.4    1952
   219.1 1961.37   229.1 1956.92     259 1931.34   268.9  1928.6   318.7 1929.17
   359.9 1915.47   368.5 1914.36   379.9 1915.24   398.4 1920.77   408.3 1920.68
   428.3  1915.4   438.2 1915.26   557.7  1924.8   627.4 1936.26   735.4 1939.22
   823.7 1944.96   853.2 1949.94   892.4 1959.79     912 1962.49   961.1 1974.34
   970.9 1972.12   990.5 1960.83  1000.4 1958.89  1049.4 1957.21  1078.9 1946.26
#Mann= 3 , 0 , 0
       0      .1       0   359.9    .045       0   379.9      .1       0
#XS Ineff= 2 , 0
                           398.3         1920.84
Permanent Ineff=
       F       F
Bank Sta=359.9,379.9
XS Rating Curve= 0 ,0
Exp/Cntr=0.3,0.1

Type RM Length L Ch R = 1 ,633.4   ,402.2,374.4,346.6
XS GIS Cut Line= 3
     1875990.917      278970.944     1876017.226      279497.131
     1876520.199      279766.415
#Sta/Elev= 30
       0 1968.25    89.5 1953.45     159 1929.54     169 1929.25   208.8 1917.36
   277.1 1911.02   297.1 1909.15   298.2 1909.08     328  1914.1   377.7 1916.49
   387.7  1918.9   427.4  1943.8     497 1957.28   605.5 1962.95   694.1 1961.33
   762.9 1966.48   821.9  1965.7   841.6 1960.96   861.3  1952.5     881 1934.47
   890.8 1933.01   910.5 1936.97   969.5 1960.05     999 1959.87  1018.7 1957.69
  1038.4 1950.21  1048.2 1941.82    1058 1930.34  1067.9 1927.79  1097.4 1927.64
#Mann= 3 , 0 , 0
       0      .1       0   277.1    .045       0   297.1      .1       0
Bank Sta=277.1,297.1
XS Rating Curve= 0 ,0
Exp/Cntr=0.3,0.1

Type RM Length L Ch R = 1 ,258.5   ,106.5,101.8,97.2
XS GIS Cut Line= 3
     1875275.922      279227.847     1875908.894      279495.583
     1876264.594      279836.317
#Sta/Elev= 30
       0 1985.15    79.7 1974.03   159.4 1969.62   189.2 1965.46     249 1951.05
     259 1946.18   288.8 1940.93   318.7 1934.11   358.6 1914.99   517.9  1911.5
   544.2 1906.51   547.8 1906.22   564.2 1907.39   607.6 1913.21   627.5 1920.35
     707 1952.63   716.8 1954.67   805.5 1954.16   864.6  1955.6   923.7 1946.96
   943.4 1945.99  1002.5 1947.25  1061.6 1950.79  1091.2 1951.44    1101 1950.16
  1110.9 1946.69  1130.6 1942.63  1140.4 1938.46  1150.3 1938.37  1179.8 1951.78
#Mann= 3 , 0 , 0
       0      .1       0   544.2    .045       0   564.2      .1       0
Bank Sta=544.2,564.2
XS Rating Curve= 0 ,0
Exp/Cntr=0.3,0.1

Type RM Length L Ch R = 1 ,156.7   ,163.5,156.7,149.8
XS GIS Cut Line= 3
     1875204.732      279418.203      1875924.37      279576.059
     1876234.791      279907.427
#Sta/Elev= 30
       0 1974.12    99.6 1973.62   199.1 1966.92     219 1962.59     239  1954.4
   298.7 1937.72   318.6  1929.3   358.4 1917.29   368.4 1917.13   388.3 1912.12
   507.8 1909.82   543.9 1905.87   547.6 1905.64   563.9 1906.62   637.2 1916.32
   647.1 1919.26   657.1 1925.43   736.8 1948.21   766.4  1945.8   786.1 1946.82
   874.9 1938.63   934.2 1940.79   973.6 1938.97  1052.6 1947.38  1072.4 1944.84
    1102 1935.12  1111.8 1935.87  1161.2    1954  1180.9 1955.28  1190.8 1953.02
#Mann= 3 , 0 , 0
       0     .06       0   543.9    .045       0   563.9     .06       0
Bank Sta=543.9,563.9
XS Rating Curve= 0 ,0
Exp/Cntr=0.3,0.1

Chan Stop Cuts=-1
Use User Specified Reach Order=0
Composite Channel Slope=5